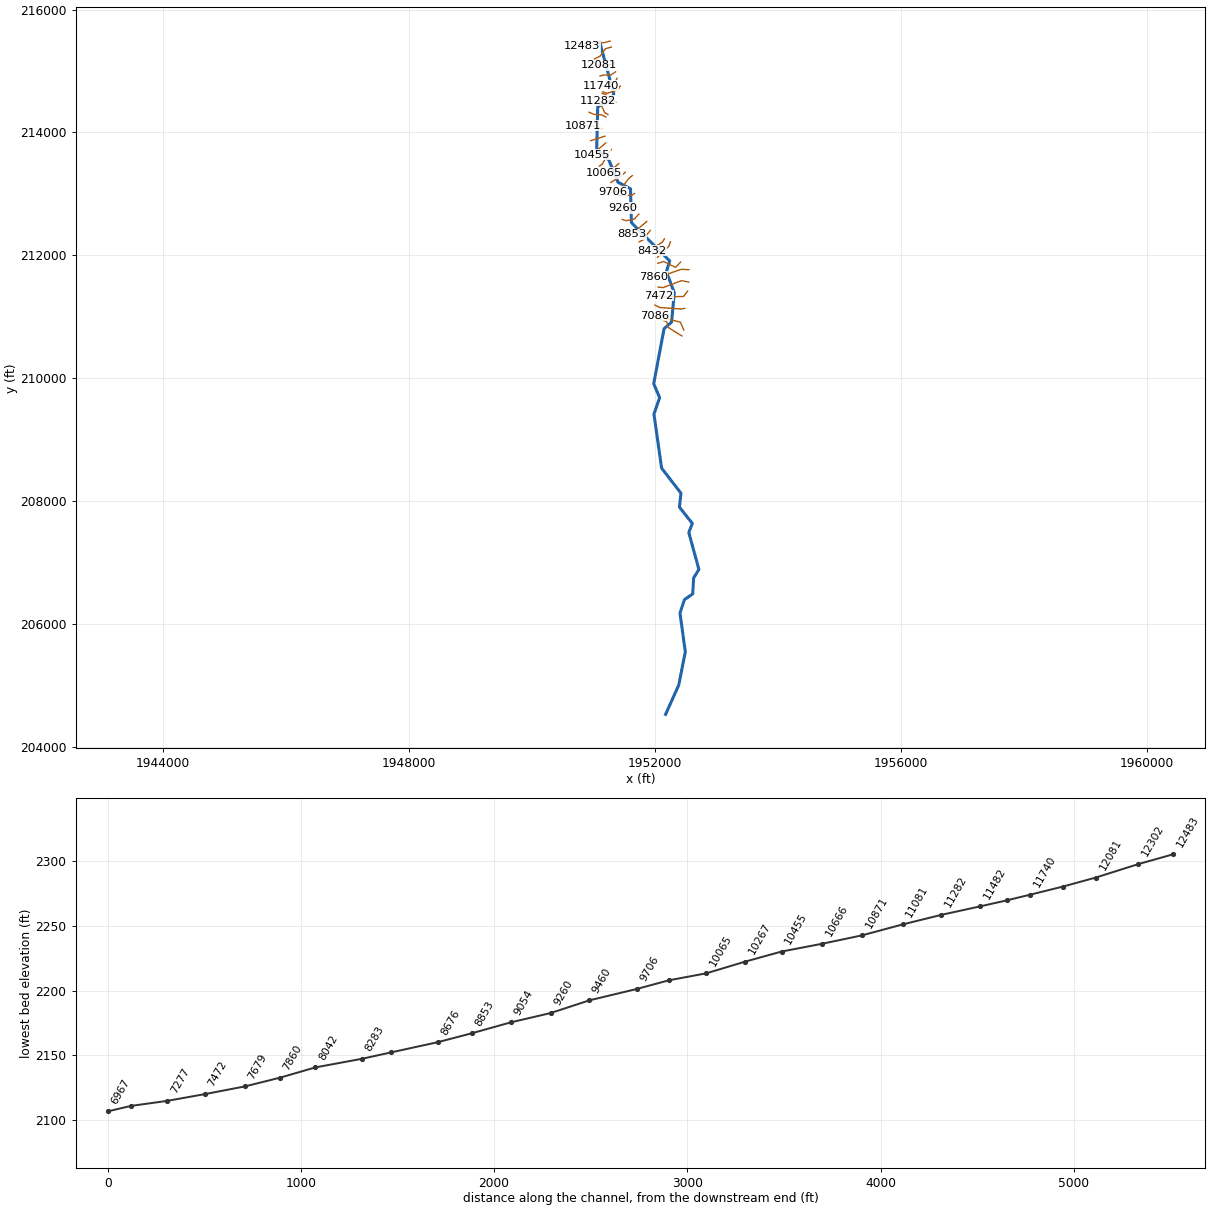
--- NFKMTNCK.prj (project) ---

Proj Title=NFKMTNCK
Current Plan=p01
Default Exp/Contr=0,0
English Units
Geom File=g01
Flow File=f01
Plan File=p01
BEGIN DESCRIPTION:
Stream Name: North Fork Mountain Creek
Flood Zone: Approximate
Summers County, West Virginia
HEC-RAS Version: 5.0.7
Hydrology Method:
regression
Model Notes:
normal depth assumed, tie-in is in mercer county
END DESCRIPTION:
DSS Export Rating Curves= 0
DSS Export Rating Curve Sorted= 0
DSS Export Volume Flow Curves= 0
DXF OffsetX= 0
DXF OffsetY= 0
DXF ScaleX= 0
DXF ScaleY= 0

--- NFKMTNCK.p01 (plan) ---

Plan Title=Floodplain
Program Version=5.07
Short Identifier=Floodplain
Geom File=g01
Flow File=f01
Subcritical Flow
K Sum by GR= 0
Std Step Tol= 0.01
Critical Tol= 0.01
Num of Std Step Trials= 20
Max Error Tol= 0.3
Flow Tol Ratio= 0.001
Split Flow NTrial= 30
Split Flow Tol= 0.02
Split Flow Ratio= 0.02
Log Output Level= 0
Friction Slope Method= 1
Unsteady Friction Slope Method= 2
Unsteady Bridges Friction Slope Method= 1
Parabolic Critical Depth
Global Vel Dist= 0 , 0 , 0
Global Log Level= 0
CheckData=True
Encroach Param=-1 ,0,0, 0
Mapping Interval=1HOUR
Computation Time Step Use Courant=        0
Computation Time Step Use Time Series=    0
Computation Time Step Count To Double=0
Computation Time Step Max Doubling=0
Computation Time Step Max Halving=0
Computation Time Step Residence Courant=0
Run HTab= 0
Run UNet= 0
Run Sediment= 0
Run PostProcess= 0
Run WQNet= 0
Run RASMapper= 0
UNET Theta= 0
UNET Theta Warmup= 0
UNET ZTol= 0
UNET ZSATol= 0
UNET MxIter= 0
UNET Max Iter WO Improvement= 0
UNET MaxInSteps= 0
UNET DtIC= 0
UNET DtMin= 0
UNET MaxCRTS= 0
UNET WFStab= 0
UNET SFStab= 0
UNET WFX= 1
UNET SFX= 1
UNET 1D Methodology=Finite Difference
UNET DSS MLevel= 1
UNET Pardiso=0
UNET DZMax Abort= 0
UNET Use Existing IB Tables= 0
UNET Froude Reduction=False
UNET Froude Limit= 0
UNET Froude Power= 0
UNET D1 Cores= 0
UNET D2 Coriolis=0
UNET D2 Cores= 0
UNET D2 Theta= 1
UNET D2 Theta Warmup= 1
UNET D2 Z Tol= 0.01
UNET D2 Volume Tol= 0.01
UNET D2 Max Iterations= 20
UNET D2 Equation= 0
UNET D2 RampUpFraction=0.1
UNET D2 TimeSlices= 1
UNET D2 BCVolumeCheck=0
UNET D1D2 MaxIter= 0
UNET D1D2 ZTol=0.01
UNET D1D2 QTol=0.1
UNET D1D2 MinQTol=1
Write IC File= 0
Write IC File at Fixed DateTime=0
Write IC File at Sim End=0
Echo Input=False
Echo Parameters=False
Echo Output=False
Write Detailed= 0
HDF Write Warmup=0
HDF Write Time Slices=0
HDF Flush=0
HDF Face Node Velocities=0
HDF Compression= 1
HDF Chunk Size= 1
HDF Spatial Parts= 1
HDF Use Max Rows=0
HDF Fixed Rows= 1
Calibration Method= 0
Calibration Iterations= 20
Calibration Max Change=0.05
Calibration Tolerance=0.2
Calibration Maximum=1.5
Calibration Minimum=0.5
Calibration Optimization Method= 1
WQ AD Non Conservative
WQ ULTIMATE=-1
WQ Max Comp Step=1HOUR
WQ Output Interval=15MIN
WQ Output Selected Increments= 0
WQ Output face flow=0
WQ Output face velocity=0
WQ Output face area=0
WQ Output face dispersion=0
WQ Output cell volume=0
WQ Output cell surface area=0
WQ Output cell continuity=0
WQ Output cumulative cell continuity=0
WQ Output face conc=0
WQ Output face dconc_dx=0
WQ Output face courant=0
WQ Output face peclet=0
WQ Output face adv mass=0
WQ Output face disp mass=0
WQ Output cell mass=0
WQ Output cell source sink temp=0
WQ Output nsm pathways=0
WQ Output nsm derived pathways=0
WQ Output MaxMinRange=-1
WQ Daily Max Min Mean=-1
WQ Daily Range=0
WQ Daily Time=0
WQ Create Restart=0
WQ Fixed Restart=0
WQ System Summary=0
WQ Write To DSS=0
WQ Use Fixed Temperature=0
Sorting and Armoring Iterations= 10
XS Update Threshold= 0.02
Bed Roughness Predictor= 0
Hydraulics Update Threshold= 0.02
Energy Slope Method= 1
Volume Change Method= 1
Sediment Retention Method= 0
XS Weighting Method= 0
Number of US Weighted Cross Sections= 1
Number of DS Weighted Cross Sections= 1
Upstream XS Weight=0
Main XS Weight=1
Downstream XS Weight=0
Number of DS XS's Weighted with US Boundary= 1
Upstream Boundary Weight= 1
Weight of XSs Associated with US Boundary= 0
Number of US XS's Weighted with DS Boundary= 1
Downstream Boundary Weight= 0.5
Weight of XSs Associated with DS Boundary= 0.5
Percentile Method= 0
Sediment Output Level= 3
Mass or Volume Output= 0
Output Increment Type= 1
Profile and TS Output Increment= 1
XS Output Flag= 0
XS Output Increment= 10
Write Gradation File= 0
Read Gradation Hotstart= 0
Write HDF5 File= 1
Write Binary Output= 1
Write DSS Sediment File= 0
SV Curve= 0
Specific Gage Flag= 0

--- NFKMTNCK.f01 (steady flow) ---

Flow Title=Flows
Program Version=5.07
Number of Profiles= 6
Profile Names=01pct,10pct,04pct,02pct,0_2pct,01plus
River Rch & RM=NFKMTNCK,Main            ,12483
     495     260     347     418     693     732
River Rch & RM=NFKMTNCK,Main            ,11619
     664     353     468     563     924     982
River Rch & RM=NFKMTNCK,Main            ,10666
     745     398     527     633    1036    1103
River Rch & RM=NFKMTNCK,Main            ,8042
     864     464     612     734    1197    1277
River Rch & RM=NFKMTNCK,Main            ,6463
     968     522     688     824    1340    1432
River Rch & RM=NFKMTNCK,Main            ,2379
    1095     594     780     933    1512    1620
Boundary for River Rch & Prof#=NFKMTNCK,Main            , 1
Up Type= 0
Dn Type= 3
Dn Slope=0.017468
Boundary for River Rch & Prof#=NFKMTNCK,Main            , 2
Up Type= 0
Dn Type= 3
Dn Slope=0.017468
Boundary for River Rch & Prof#=NFKMTNCK,Main            , 3
Up Type= 0
Dn Type= 3
Dn Slope=0.017468
Boundary for River Rch & Prof#=NFKMTNCK,Main            , 4
Up Type= 0
Dn Type= 3
Dn Slope=0.017468
Boundary for River Rch & Prof#=NFKMTNCK,Main            , 5
Up Type= 0
Dn Type= 3
Dn Slope=0.017468
Boundary for River Rch & Prof#=NFKMTNCK,Main            , 6
Up Type= 0
Dn Type= 3
Dn Slope=0.017468
DSS Import GetInterval= 0
DSS Import GetPeak= 0
DSS Import FillOption= 0

--- NFKMTNCK.g01 (geometry) ---

Geom Title=Geometry
Program Version=5.07

River Reach=NFKMTNCK        ,Main
Reach XY= 30
     1951102.271      215472.018     1951330.978      214626.574
     1951289.046       214530.52     1951069.756      214417.369
1951053.60716642213727.332618658     1951251.415      213550.557
     1951400.026      213190.141     1951603.498      213083.196
     1951618.679      212532.089     1952240.998      211909.585
     1952187.526      211734.585     1952315.768      211391.238
     1952271.554      210914.446     1952149.332      210807.502
     1951980.996      209911.499 1952076.8573182209684.028417364
     1951984.815      209414.624     1952109.054      208538.057
     1952425.026      208128.335     1952398.637      207903.335
     1952609.054      207638.752      1952552.11      207489.446
     1952715.998      206888.752     1952630.582      206750.557
     1952615.999      206491.529     1952480.154      206396.674
      1952408.36      206179.724     1952495.165      205545.696
     1952388.915      205008.891     1952174.082      204529.645

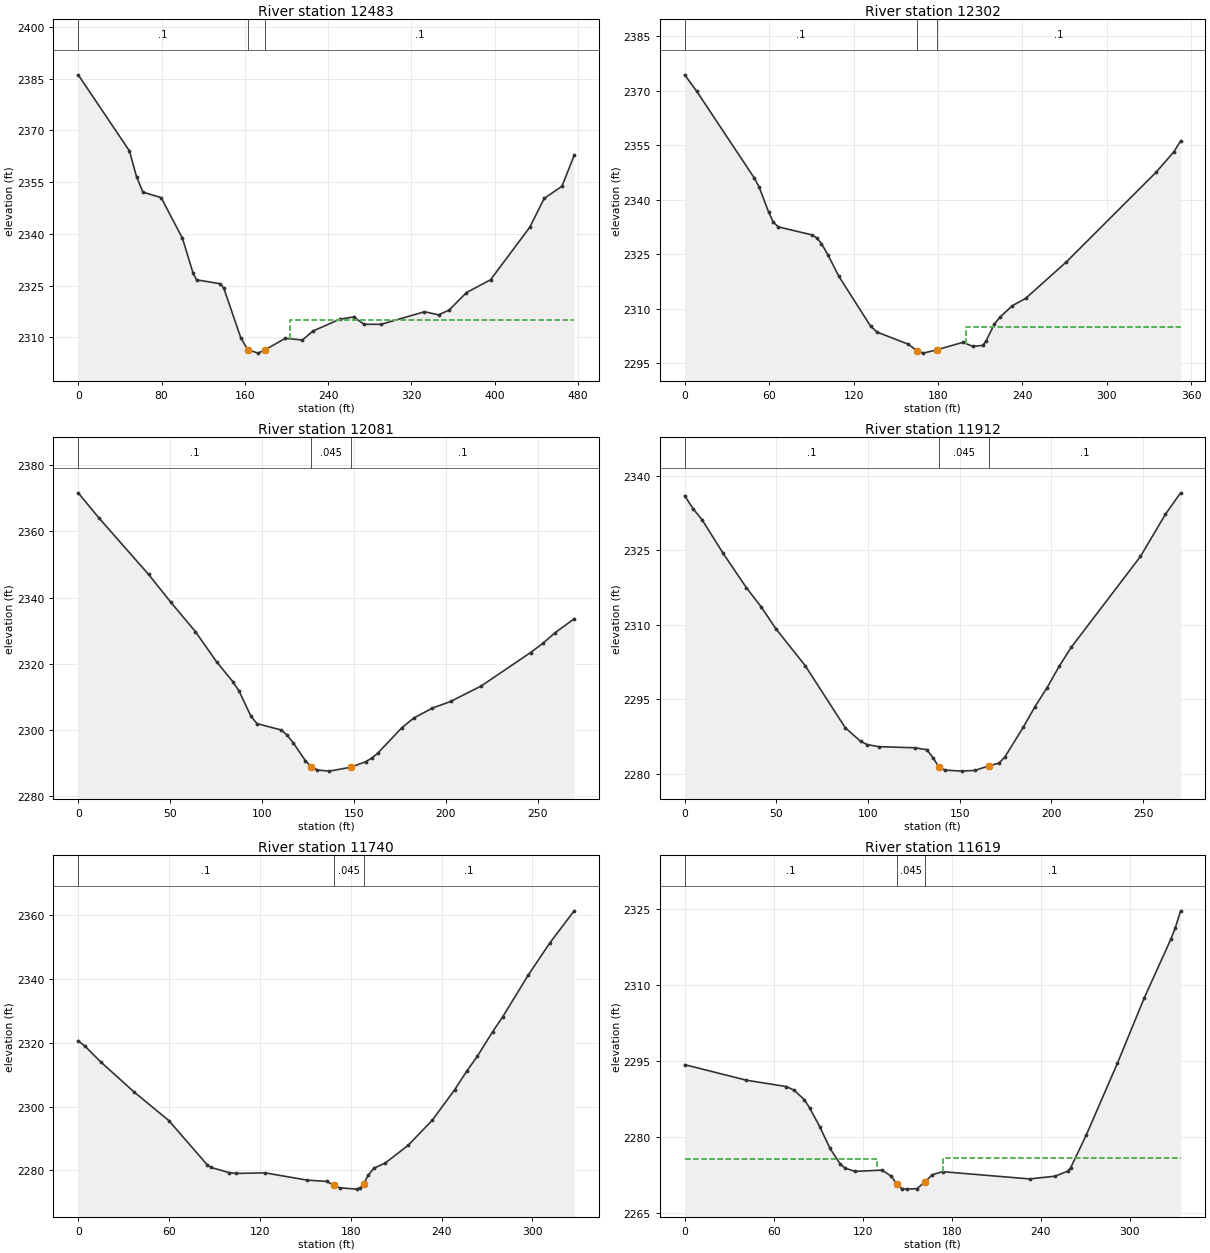
Type RM Length L Ch R = 1 ,12483   ,181,181,181
XS GIS Cut Line= 4
1951271.73915825215487.1751359351951163.12538491215459.117041691
1950896.48949272215465.9310085811950817.13872813215409.693875513
#Sta/Elev= 30
       0 2386.14    49.2 2364.07      56 2356.61    62.1 2352.14    79.7 2350.52
   100.1 2338.73   110.2 2328.76   113.6 2326.72   136.5 2325.55   139.8 2324.27
   156.2 2309.82   162.8 2306.46   172.6 2305.45   179.2 2306.37   198.9 2309.75
   215.3 2309.25   225.2 2311.83   251.4 2315.31   264.5 2315.94   274.4 2313.82
   290.8  2313.8   332.5 2317.45     346 2316.55   356.1 2317.92   372.8    2323
   395.9 2326.71   433.6 2341.96   447.4  2350.3   464.4 2353.81   476.2 2362.75
#Mann= 3 ,-1 , 0
       0      .1       0   162.8    .045       0   179.2      .1       0
#XS Ineff= 2 , 0
                             203            2315
Permanent Ineff=
       F       F
Bank Sta=162.8,179.2
XS Rating Curve= 0 ,0
Exp/Cntr=0.3,0.1

Type RM Length L Ch R = 1 ,12302   ,235,220.4,208.7
XS GIS Cut Line= 4
1951291.35585613215389.7472821471951196.60480182215363.115478569
1951104.62301181215239.604000062 1951014.7047481215195.825978276
#Sta/Elev= 30
       0 2374.32     8.6 2369.78    49.5 2345.95    52.9 2343.48    59.7 2336.55
    63.1 2333.79    66.5 2332.54    90.3 2330.34    93.8 2329.56    97.2 2327.93
   101.9 2324.77   109.6 2318.92   132.1 2305.27   136.8  2303.6   158.7 2300.32
   164.9 2298.55   169.6 2297.84   179.1 2298.75   197.7 2300.81   204.8 2299.69
   211.9 2299.97   214.2 2301.21   220.1 2305.87   224.1 2307.76   232.9 2310.89
   242.3 2312.88   271.3 2322.94   334.9 2347.52   347.4 2353.08   352.4 2356.11
#Mann= 3 ,-1 , 0
       0      .1       0   164.9    .045       0   179.1      .1       0
#XS Ineff= 2 , 0
                             200            2305
Permanent Ineff=
       F       F
Bank Sta=164.9,179.1
XS Rating Curve= 0 ,0
Exp/Cntr=0.3,0.1

Type RM Length L Ch R = 1 ,12081   ,168.8,169.6,170.6
XS GIS Cut Line= 4
1951347.03854295215134.6606743961951283.46514145215103.667991901
1951164.15625388215107.3700618851951085.97314763215091.253560468
#Sta/Elev= 30
       0 2371.69    11.2 2364.13    38.3 2346.99    50.5 2338.49    63.8 2329.67
    75.3 2320.55    84.2 2314.49    87.5 2311.73      94 2304.07    97.3 2301.82
   110.5 2299.89   113.7 2298.33     117 2296.03   123.6 2290.63   126.9 2288.65
   130.2 2287.78   136.7 2287.44   148.6 2288.66   156.4 2290.29   159.7 2291.37
     163 2292.85   176.1 2300.57   182.7 2303.54   192.6 2306.48   202.7 2308.54
   219.4 2313.25   246.2 2323.34   252.9 2326.14   259.6 2329.36   269.9 2333.56
#Mann= 3 , 0 , 0
       0      .1       0   126.9    .045       0   148.6      .1       0
Bank Sta=126.9,148.6
XS Rating Curve= 0 ,0
Exp/Cntr=0.3,0.1

Type RM Length L Ch R = 1 ,11912   ,164.1,171.3,180.2
XS GIS Cut Line= 4
1951359.90145504214988.3939381151951288.18089391214938.027186727
1951167.33973711214935.6693104971951107.82705972214918.161586489
#Sta/Elev= 30
       0 2335.96     4.5 2333.37     9.6 2331.05      21 2324.33    33.7 2317.41
    41.7 2313.58    49.7 2309.18    65.8 2301.69    87.6 2289.21      96 2286.47
    99.6 2285.82   105.8 2285.41   125.5 2285.18   132.1 2284.79   135.4 2283.22
   138.6 2281.34   141.9 2280.69   151.1 2280.48   158.3 2280.63   165.9 2281.53
   171.5 2282.12   174.7 2283.36   184.6 2289.28   191.1 2293.48   197.7 2297.31
   204.3 2301.62   210.9 2305.45   248.6 2323.72   262.2 2332.21   270.5 2336.53
#Mann= 3 ,-1 , 0
       0      .1       0   138.6    .045       0   165.9      .1       0
Bank Sta=138.6,165.9
XS Rating Curve= 0 ,0
Exp/Cntr=0.3,0.1

Type RM Length L Ch R = 1 ,11740   ,124.4,121.5,118.4
XS GIS Cut Line= 4
1951384.49272122214882.3640330611951357.79718961214828.739623457
1951206.95887168214741.8723459891951115.81225417214763.396821385
#Sta/Elev= 30
       0  2320.6     4.4 2318.94    14.9 2313.97    36.9 2304.57    59.9  2295.6
    85.2 2281.79    87.8 2280.93    99.8 2279.31   104.4 2279.07   123.4 2279.26
     151 2276.99   164.1 2276.58   168.8  2275.4   172.6 2274.58   183.9 2274.16
   186.3  2274.6   188.7 2275.92   191.5 2278.51   195.3  2280.7   202.9 2282.36
     218 2287.89     234  2295.8   248.7 2305.28   256.8 2311.21   263.6 2315.71
   273.7 2323.39   280.4 2328.08   297.3 2341.17   311.4 2351.13   327.6 2361.26
#Mann= 3 ,-1 , 0
       0      .1       0   168.8    .045       0   188.7      .1       0
Bank Sta=168.8,188.7
XS Rating Curve= 0 ,0
Exp/Cntr=0.3,0.1

Type RM Length L Ch R = 1 ,11619   ,151.1,136.5,121
XS GIS Cut Line= 4
1951436.76646353214756.5252947581951399.09939075214694.454202997
 1951222.4355142 214636.627288451951151.34554586 214663.15339604
#Sta/Elev= 30
       0 2294.29    41.6 2291.22    68.5 2289.97    73.8 2289.25    80.7 2287.38
    84.2 2285.78    91.1 2282.05      98 2277.77   104.9  2274.7   108.3 2273.87
   114.9 2273.25   133.1  2273.5   139.4 2272.28   142.9 2270.77   146.3 2269.87
   149.8 2269.75   156.7 2269.84   161.8 2271.12     167  2272.6   173.9 2273.19
   232.6 2271.76   249.9 2272.31   258.5 2273.32   260.3 2273.99   270.8 2280.43
   291.8 2294.58     310 2307.52   327.9 2319.08   330.8 2321.25   334.4 2324.61
#Mann= 3 ,-1 , 0
       0      .1       0   142.9    .045       0   161.8      .1       0
#XS Ineff= 2 , 0
          129.55 2275.74  174.31         2275.92
Permanent Ineff=
       F       F
Bank Sta=142.9,161.8
XS Rating Curve= 0 ,0
Exp/Cntr(USF)=0,0
Exp/Cntr=0.3,0.1

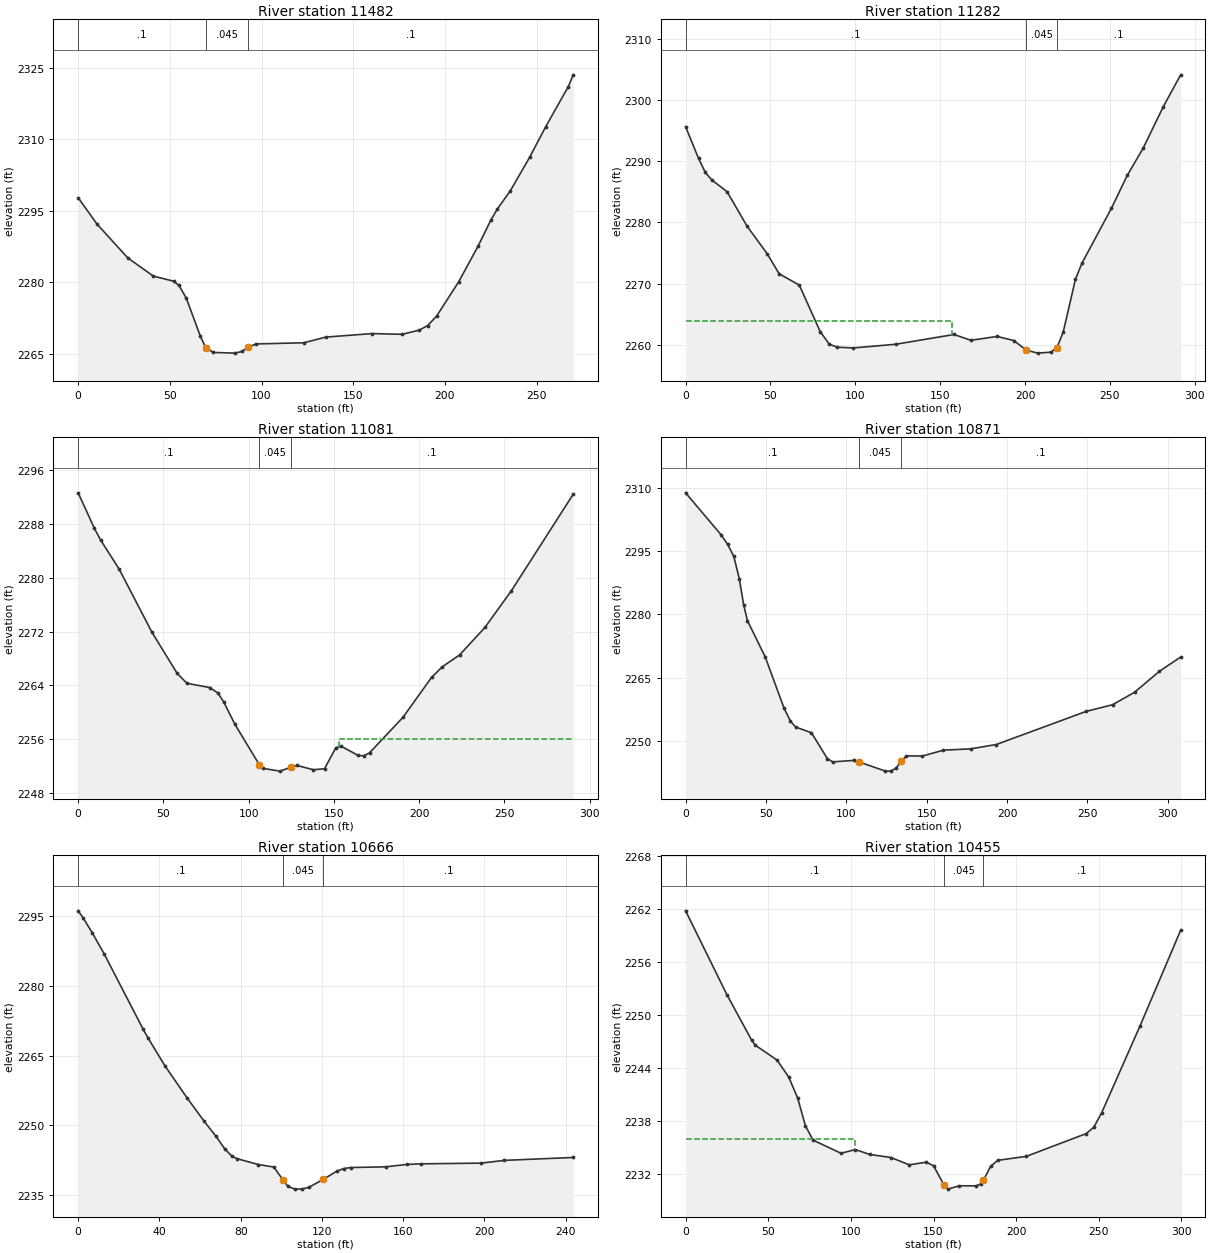
Type RM Length L Ch R = 1 ,11482   ,208.5,200.3,193.1
XS GIS Cut Line= 3
1951363.51927923214491.1531603031951210.74364137214610.118003504
1951139.56929108214637.780162467
#Sta/Elev= 30
       0 2297.74    10.4 2292.16    27.1 2285.11      41 2281.31      52 2280.24
      55 2279.34      59 2276.65    66.7 2268.64    69.6 2266.28    73.7  2265.3
    85.3 2265.15    89.4  2265.5    92.5 2266.37    97.1 2267.08     123 2267.32
   135.2 2268.52   160.4 2269.25   176.7  2269.1     186 2269.97   190.6 2270.93
   195.5 2272.92   207.5 2280.09   218.1 2287.58   225.1 2293.07   228.6 2295.36
   235.7  2299.2   246.2 2306.21     255 2312.65   267.3 2321.04     270 2323.53
#Mann= 3 ,-1 , 0
       0      .1       0    69.6    .045       0    92.5      .1       0
Bank Sta=69.6,92.5
XS Rating Curve= 0 ,0
Exp/Cntr=0.3,0.1

Type RM Length L Ch R = 1 ,11282   ,180.9,200.6,211.7
XS GIS Cut Line= 4
1951236.98289808214289.9771209361951182.66593261214326.158304983
1951111.08455696214477.8510717271951065.09917365214514.389680064
#Sta/Elev= 30
       0 2295.68     7.6 2290.49    11.6  2288.2    15.5 2286.93    24.4 2285.05
    36.2  2279.4      48 2274.91    55.1 2271.61      67 2269.75    79.3 2262.15
    84.6  2260.1    89.2 2259.59    98.9 2259.47   123.7 2260.07   158.2 2261.67
   168.1 2260.72   183.5 2261.35   193.4 2260.68   200.7 2259.11   207.5 2258.62
   215.2 2258.78   218.8  2259.5   222.5 2262.07   229.7 2270.71   233.5 2273.32
   250.9 2282.32   260.2 2287.69   269.6 2292.15   281.5 2298.97   291.7 2304.16
#Mann= 3 ,-1 , 0
       0      .1       0   200.7    .045       0   218.8      .1       0
#XS Ineff= 2 , 0
          156.85 2263.94
Permanent Ineff=
       F       F
Bank Sta=200.7,218.8
XS Rating Curve= 0 ,0
Exp/Cntr=0.3,0.1

Type RM Length L Ch R = 1 ,11081   ,206.9,210,210.2
XS GIS Cut Line= 4
1951203.16670258214252.0586258571951126.41533895214287.803530942
1951007.59362252214294.3269758751950928.48954496214329.810026022
#Sta/Elev= 30
       0 2292.65     9.5 2287.37    13.1 2285.65      24 2281.31    43.3 2271.88
    58.1 2265.76    63.8 2264.29    77.1 2263.66    81.9 2262.86    85.4  2261.5
      92 2258.16   106.3 2252.15   108.4 2251.62   118.3 2251.21   124.9  2251.8
   128.2 2252.06     138 2251.42   144.5 2251.56   151.2 2254.72   154.4  2254.9
   164.3 2253.54   167.6  2253.5   170.9 2253.93   190.6 2259.24   207.3 2265.16
   213.7 2266.77   223.7  2268.5   238.6  2272.6   254.1 2278.06   290.4 2292.44
#Mann= 3 ,-1 , 0
       0      .1       0   106.3    .045       0   124.9      .1       0
#XS Ineff= 2 , 0
                          152.96         2255.97
Permanent Ineff=
       F       F
Bank Sta=106.3,124.9
XS Rating Curve= 0 ,0
Exp/Cntr=0.3,0.1

Type RM Length L Ch R = 1 ,10871   ,197,205.6,210.8
XS GIS Cut Line= 3
1951131.11379683214059.7128045041951076.56150225214095.086434421
1950833.97495847214108.482087906
#Sta/Elev= 30
       0 2308.88    22.2 2298.85    26.1 2296.67      30 2293.78    33.4 2288.46
    36.1 2282.32    38.5 2278.49    49.5 2269.93    61.3 2257.68    65.2 2254.66
    68.4 2253.26    78.3 2251.89    88.2 2245.75    91.4 2244.98   104.6 2245.33
   107.9 2244.97   124.3 2242.78   127.6 2242.79   130.9 2243.47   134.2 2245.15
   137.4 2246.41   147.3 2246.36   160.4 2247.76   177.3 2248.07   193.3  2249.1
   249.2 2256.97   265.6 2258.55   279.3  2261.5   294.8  2266.5     308 2269.88
#Mann= 3 ,-1 , 0
       0      .1       0   107.9    .045       0   134.2      .1       0
Bank Sta=107.9,134.2
XS Rating Curve= 0 ,0
Exp/Cntr=0.3,0.1

Type RM Length L Ch R = 1 ,10666   ,201.2,210.7,215.6
XS GIS Cut Line= 2
1951187.96225955213939.855615345 1950955.5640279213866.530261825
#Sta/Elev= 30
       0 2296.09     2.4  2294.6     6.9  2291.4    12.9 2286.75    31.9 2270.72
    34.4 2268.76    42.8 2262.73    53.7 2255.84    61.9 2250.95    67.8 2247.67
    72.2 2244.93    75.7 2243.37    78.2 2242.85    88.7 2241.58    96.3 2241.05
     1012238.181   103.2 2236.92   106.6  2236.3   110.1 2236.33   113.5 2236.67
   120.7 2238.41   127.3 2240.15   130.7 2240.72   134.2 2240.94   151.4 2241.09
   161.7  2241.6   168.6 2241.73   198.5 2241.89   209.8 2242.48   243.7  2243.1
#Mann= 3 ,-1 , 0
       0      .1       0     101    .045       0   120.7      .1       0
Bank Sta=101,120.7
XS Rating Curve= 0 ,0
Exp/Cntr=0.3,0.1

Type RM Length L Ch R = 1 ,10455   ,181.6,187.9,192.5
XS GIS Cut Line= 2
1951200.47476527213829.6310081591950972.53590502213635.385734147
#Sta/Elev= 30
       0 2261.78      25 2252.28    39.9 2247.15    42.2 2246.56    55.2  2244.9
    62.4 2242.96    67.8 2240.57    72.5 2237.43    77.1 2235.82      94 2234.33
   102.7 2234.75   111.3  2234.2   124.2 2233.85   135.3 2233.02   145.7 2233.32
     150 2232.91   156.2 2230.79   158.7 2230.27   165.6 2230.65   175.9 2230.64
   178.7 2230.87   180.2 2231.28   184.5 2232.84   188.8 2233.53   206.1 2233.98
   242.4 2236.56     247 2237.29   251.7 2238.91   274.9 2248.74   299.5 2259.58
#Mann= 3 ,-1 , 0
       0      .1       0   156.2    .045       0   180.2      .1       0
#XS Ineff= 2 , 0
          102.25 2235.94
Permanent Ineff=
       F       F
Bank Sta=156.2,180.2
XS Rating Curve= 0 ,0
Exp/Cntr=0.3,0.1

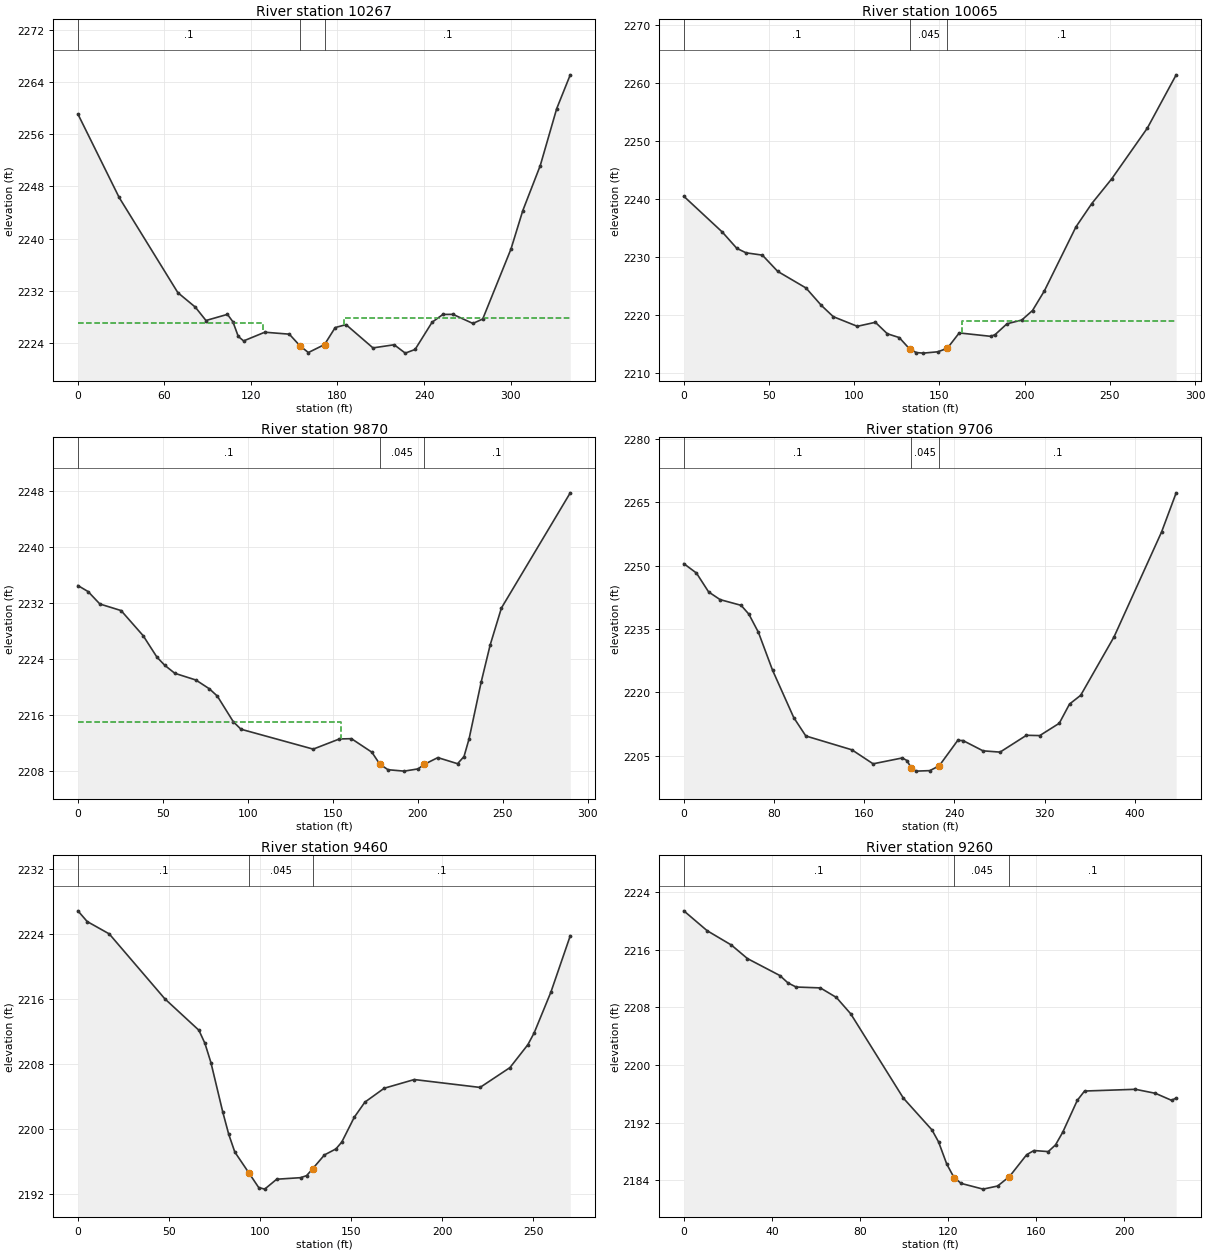
Type RM Length L Ch R = 1 ,10267   ,212.4,202.5,193.1
XS GIS Cut Line= 4
1951292.78510432213723.0605352931951248.19062337213675.268452035
1951145.31814816213486.0488313481951094.41034768213453.068215356
#Sta/Elev= 30
       0 2259.08    28.6 2246.32    69.3 2231.76    81.4 2229.55    88.8  2227.5
   103.7 2228.44   107.5  2227.3   111.2 2225.06   114.9 2224.38   129.6 2225.71
   146.6 2225.41     154 2223.62   159.8  2222.6     171 2223.82   178.4 2226.42
   185.9 2226.87   204.6 2223.31   219.3 2223.79     227 2222.51   233.8 2223.07
   245.6 2227.24   253.1 2228.43   260.1 2228.44   273.9 2227.05   280.7 2227.73
   300.3 2238.44   308.5 2244.32   320.6  2251.2     332 2259.91   341.4 2265.08
#Mann= 3 ,-1 , 0
       0      .1       0     154    .045       0     171      .1       0
#XS Ineff= 2 , 0
          128.17  2227.1  184.17         2227.85
Permanent Ineff=
       F       F
Bank Sta=154,171
XS Rating Curve= 0 ,0
Exp/Cntr=0.3,0.1

Type RM Length L Ch R = 1 ,10065   ,191.5,194.4,198.1
XS GIS Cut Line= 4
1951412.65259894213494.6385983541951350.59509988213440.678713091
1951239.18805349213397.553404811 1951173.7602936213339.898850265
#Sta/Elev= 30
       0 2240.45    22.6 2234.28    31.1 2231.48    36.5 2230.71    46.1 2230.31
    55.1 2227.51    71.7 2224.65    80.7 2221.65    87.7 2219.71   101.8 2218.05
   112.4 2218.74   119.4 2216.77   126.4 2216.11   132.7 2214.08   136.4 2213.53
   140.5 2213.43     149 2213.66   154.6 2214.26   161.6 2216.91   180.2 2216.32
   182.7 2216.63   189.6 2218.48   198.3 2219.13   204.6 2220.77   211.6 2224.17
   230.1 2235.18   239.4  2239.2   251.1 2243.46     272  2252.2   288.9 2261.37
#Mann= 3 ,-1 , 0
       0      .1       0   132.7    .045       0   154.6      .1       0
#XS Ineff= 2 , 0
                          163.27         2218.89
Permanent Ineff=
       F       F
Bank Sta=132.7,154.6
XS Rating Curve= 0 ,0
Exp/Cntr=0.3,0.1

Type RM Length L Ch R = 1 ,9870    ,157.6,163.9,171.1
XS GIS Cut Line= 3
1951516.68484497213354.0836914861951451.11527271213290.594647719
1951282.44629584213186.175898705
#Sta/Elev= 30
       0 2234.48       6 2233.62    12.9 2231.85    25.4 2230.91    38.4 2227.32
    46.5 2224.26    51.1  2223.1      57 2221.96    69.4    2221    77.3 2219.75
      82 2218.71    91.4 2215.05    95.9 2213.98   138.4 2211.14   153.8 2212.59
   160.9 2212.63   172.9  2210.7   177.6 2208.99   182.4  2208.2   191.9    2208
   200.1 2208.32   203.6 2208.95   211.7 2209.93   223.3 2209.06   227.1 2210.08
   230.1 2212.62   237.2 2220.71   242.5 2226.01   249.1 2231.27   289.6 2247.71
#Mann= 3 ,-1 , 0
       0      .1       0   177.6    .045       0   203.6      .1       0
#XS Ineff= 2 , 0
             155    2215
Permanent Ineff=
       F       F
Bank Sta=177.6,203.6
XS Rating Curve= 0 ,0
Exp/Cntr=0.3,0.1

Type RM Length L Ch R = 1 ,9706    ,260.1,246.9,215.9
XS GIS Cut Line= 4
1951632.61504435213297.9592430791951567.92315122213244.295128076
1951420.16963642213043.9688352811951316.72771956213036.422387773
#Sta/Elev= 30
       0 2250.47    11.2 2248.25      22 2243.78    32.2 2241.96    50.8 2240.61
    57.7 2238.52    66.2  2234.2    78.7 2225.26    97.5 2214.05   108.2  2209.7
   149.1 2206.42   167.9 2203.11   193.8  2204.5   197.9 2203.89   201.9 2202.05
     206 2201.38   218.2  2201.5   226.5 2202.63   242.9 2208.63   247.6 2208.62
   265.4 2206.18   280.5 2205.88   303.9 2209.86   315.7 2209.79     333  2212.7
   342.1 2217.25     352 2219.32   381.6 2233.15   423.8    2258   436.7 2267.23
#Mann= 3 ,-1 , 0
       0      .1       0   201.9    .045       0   226.5      .1       0
Bank Sta=201.9,226.5
XS Rating Curve= 0 ,0
Exp/Cntr=0.3,0.1

Type RM Length L Ch R = 1 ,9460    ,197.5,199.4,198.9
XS GIS Cut Line= 3
1951667.86372158213008.3504461831951624.91432963212977.851839232
1951407.46847622212971.500822761
#Sta/Elev= 30
       0  2226.8     5.1 2225.48    17.2 2223.96    47.7 2215.97    66.4  2212.1
    69.7 2210.49      73 2208.12    79.5 2202.03    82.8 2199.27    86.1 2197.11
    93.8 2194.55    99.2 2192.74   102.5 2192.54   109.1 2193.76   122.2 2193.95
   125.5  2194.2   128.8 2195.04   135.3 2196.75   141.6 2197.49   144.8 2198.33
   151.7  2201.4   157.5 2203.25   168.1 2204.96   184.6 2206.03   220.7 2205.06
   237.1  2207.5   246.9 2210.31   250.4 2211.78   259.6 2216.81   270.2 2223.73
#Mann= 3 ,-1 , 0
       0      .1       0    93.8    .045       0   128.8      .1       0
Bank Sta=93.8,128.8
XS Rating Curve= 0 ,0
Exp/Cntr=0.3,0.1

Type RM Length L Ch R = 1 ,9260    ,203.8,206.5,207.4
XS GIS Cut Line= 3
 1951696.1359779      212819.1751951627.77914926212784.953984837
1951481.19587871212772.062296549
#Sta/Elev= 30
       0  2221.4    10.6 2218.64    21.6 2216.65    28.9 2214.77    43.6 2212.42
    47.3 2211.39      51 2210.82      62  2210.7    69.3 2209.37    75.8  2207.1
    99.7  2195.4   112.7 2190.98   115.7 2189.31   119.4 2186.25   122.7 2184.37
     126 2183.55   135.9 2182.76   142.5 2183.19   147.9 2184.51   155.7 2187.54
     159 2188.12   165.5 2187.97   168.8  2188.9   172.1 2190.67   178.7 2195.09
     182 2196.38   205.1 2196.62   214.2 2196.06   221.5 2195.09   223.6 2195.41
#Mann= 3 ,-1 , 0
       0      .1       0   122.7    .045       0   147.9      .1       0
Bank Sta=122.7,147.9
XS Rating Curve= 0 ,0
Exp/Cntr=0.3,0.1

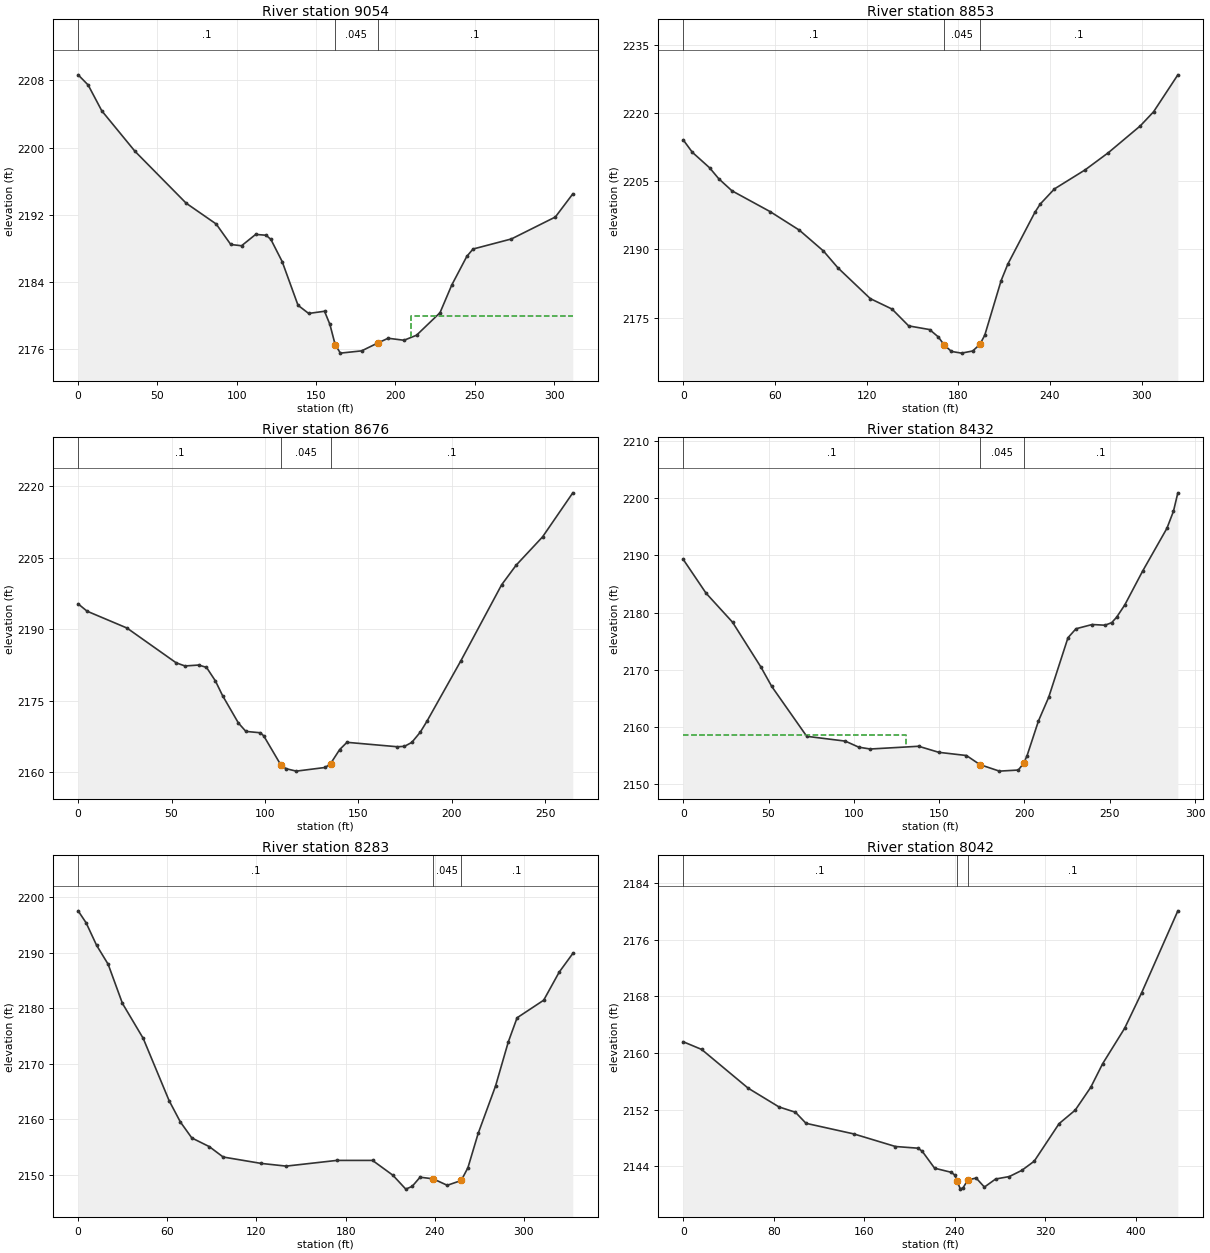
Type RM Length L Ch R = 1 ,9054    ,190.9,200.5,210.3
XS GIS Cut Line= 4
1951739.21005384212671.7881819791951665.61097151212590.078759493
1951529.89781225212564.362874119 1951469.4777547212584.634539542
#Sta/Elev= 30
       0 2208.66     6.3 2207.45    14.9 2204.38    35.8 2199.57    68.1 2193.39
      87 2190.92    96.2 2188.48     103 2188.33   111.9 2189.68   118.5 2189.58
   121.5 2189.08   128.6 2186.45   138.6 2181.25   145.3 2180.28   155.3 2180.54
   158.7 2178.97     162 2176.57   165.3 2175.56   178.7 2175.83   188.7 2176.75
   195.4 2177.33   205.4 2177.09   213.3 2177.69   228.1 2180.37   235.5 2183.66
     245 2187.07   248.9 2187.94   273.1 2189.14   300.8 2191.75   311.8  2194.5
#Mann= 3 ,-1 , 0
       0      .1       0     162    .045       0   188.7      .1       0
#XS Ineff= 2 , 0
                             210            2180
Permanent Ineff=
       F       F
Bank Sta=162,188.7
XS Rating Curve= 0 ,0
Exp/Cntr=0.3,0.1

Type RM Length L Ch R = 1 ,8853    ,171.3,176.9,182.5
XS GIS Cut Line= 2
1951868.42399731212552.4261257031951622.04951002 212342.33935359
#Sta/Elev= 30
       0 2214.09       6 2211.35    17.3 2207.94    23.3 2205.53    31.9 2202.89
    56.9 2198.31      76 2194.24    91.8 2189.65   101.3 2185.94   122.5 2179.17
   136.7 2176.88   147.6 2173.18   161.3 2172.37     167 2170.75   170.9 2168.96
   175.6 2167.56   182.2 2167.19   189.5 2167.66   194.2 2169.11   197.4 2171.13
   208.1 2183.13   212.5 2186.77   230.2 2198.14   233.7 2199.97     243  2203.3
   263.1 2207.49   278.3 2211.27   299.2 2217.16   307.9 2220.26   323.8 2228.39
#Mann= 3 ,-1 , 0
       0      .1       0   170.9    .045       0   194.2      .1       0
Bank Sta=170.9,194.2
XS Rating Curve= 0 ,0
Exp/Cntr=0.3,0.1

Type RM Length L Ch R = 1 ,8676    ,251.5,244.7,236
XS GIS Cut Line= 4
1951924.20216142212405.1236930841951868.04875949212337.305895563
1951818.28965397212256.8722349351951744.17349523212221.343705648
#Sta/Elev= 30
       0 2195.33     4.8 2193.79    26.1 2190.27    52.5 2182.96    57.2 2182.31
    64.5  2182.5    68.7 2182.02    73.5 2179.16    77.3  2176.1    85.8 2170.34
    89.8 2168.59    97.6  2168.3    99.4 2167.62   108.5 2161.56   111.3 2160.77
   116.8 2160.26   132.3 2161.03   135.1 2161.82     140 2164.78   143.9  2166.3
   170.9 2165.37   174.7 2165.46   178.6 2166.28   183.1  2168.4   186.7 2170.71
   204.9 2183.41   226.7 2199.33   234.4 2203.41   248.6 2209.37   264.8 2218.61
#Mann= 3 ,-1 , 0
       0      .1       0   108.5    .045       0   135.1      .1       0
Bank Sta=108.5,135.1
XS Rating Curve= 0 ,0
Exp/Cntr=0.3,0.1

Type RM Length L Ch R = 1 ,8432    ,145.3,148.3,151.6
XS GIS Cut Line= 4
1952154.59451744212268.4874335631952124.34788334212219.152109942
1951970.60256375212116.4960735691951945.77412704212076.388598892
#Sta/Elev= 30
       0 2189.32    13.4  2183.4    28.9 2178.33    45.6 2170.45    51.9 2167.08
    72.4 2158.36      95 2157.52   102.9 2156.46   109.6 2156.14     138 2156.62
   149.8 2155.56     166    2155   173.9 2153.41   185.3 2152.27   196.4 2152.46
   199.5 2153.64   201.5 2154.95   208.2 2161.05   214.2 2165.19   225.5 2175.61
   230.2 2177.18   239.7 2177.92   247.2  2177.8   251.1 2178.24     254 2179.19
   258.8 2181.35   269.2 2187.24   283.5 2194.76   287.3 2197.72   289.9 2200.96
#Mann= 3 ,-1 , 0
       0      .1       0   173.9    .045       0   199.5      .1       0
#XS Ineff= 2 , 0
          130.65 2158.59
Permanent Ineff=
       F       F
Bank Sta=173.9,199.5
XS Rating Curve= 0 ,0
Exp/Cntr=0.3,0.1

Type RM Length L Ch R = 1 ,8283    ,253.8,241.3,233.8
XS GIS Cut Line= 3
1952252.07253205212219.4422273431952225.40050137212145.911044679
1952042.70052418211968.480393216
#Sta/Elev= 30
       0 2197.59     5.4 2195.41    12.4 2191.38    20.2 2187.95    29.8  2180.9
    43.8 2174.58    61.2 2163.37    68.8 2159.51    76.5 2156.63    88.3 2155.06
    97.6 2153.19   123.1 2152.04     140 2151.55   174.1 2152.58   198.1 2152.58
   211.8 2149.91   220.5  2147.4   224.8  2147.9   230.1 2149.55   238.9 2149.26
   248.4 2148.09   257.8 2148.96   262.3 2151.25   269.2 2157.44   280.9 2165.99
   289.5 2173.96   295.4  2178.3   313.3 2181.47   323.7 2186.52   332.9  2189.9
#Mann= 3 ,-1 , 0
       0      .1       0   238.9    .045       0   257.8      .1       0
#XS Ineff= 2 , 0
          176.48 2152.21
Permanent Ineff=
       F       F
Bank Sta=238.9,257.8
XS Rating Curve= 0 ,0
Exp/Cntr=0.3,0.1

Type RM Length L Ch R = 1 ,8042    ,171.7,182,189.5
XS GIS Cut Line= 4
1952418.83457757 211891.502916121952334.91212539211804.230735019
1952139.72871204211901.2385569581952046.81934489211870.324976247
#Sta/Elev= 30
       0 2161.59    16.3  2160.5    57.4 2155.02    84.6 2152.37    99.2 2151.61
   108.5 2150.05   150.7 2148.55   187.5 2146.77   207.5 2146.53   211.2 2146.09
   222.1  2143.7   236.8 2143.12     240 2142.72   241.8 2141.91   244.9 2140.74
   247.4 2140.97   251.5 2142.04   258.8 2142.31   266.1 2141.03     276 2142.17
   288.1 2142.52   299.1 2143.39   310.1 2144.69   332.1 2150.01   346.3 2151.91
   360.1 2155.16   370.5 2158.47     390  2163.5   405.1 2168.55     437 2180.11
#Mann= 3 ,-1 , 0
       0      .1       0   241.8    .045       0   251.5      .1       0
Bank Sta=241.8,251.5
XS Rating Curve= 0 ,0
Exp/Cntr=0.3,0.1

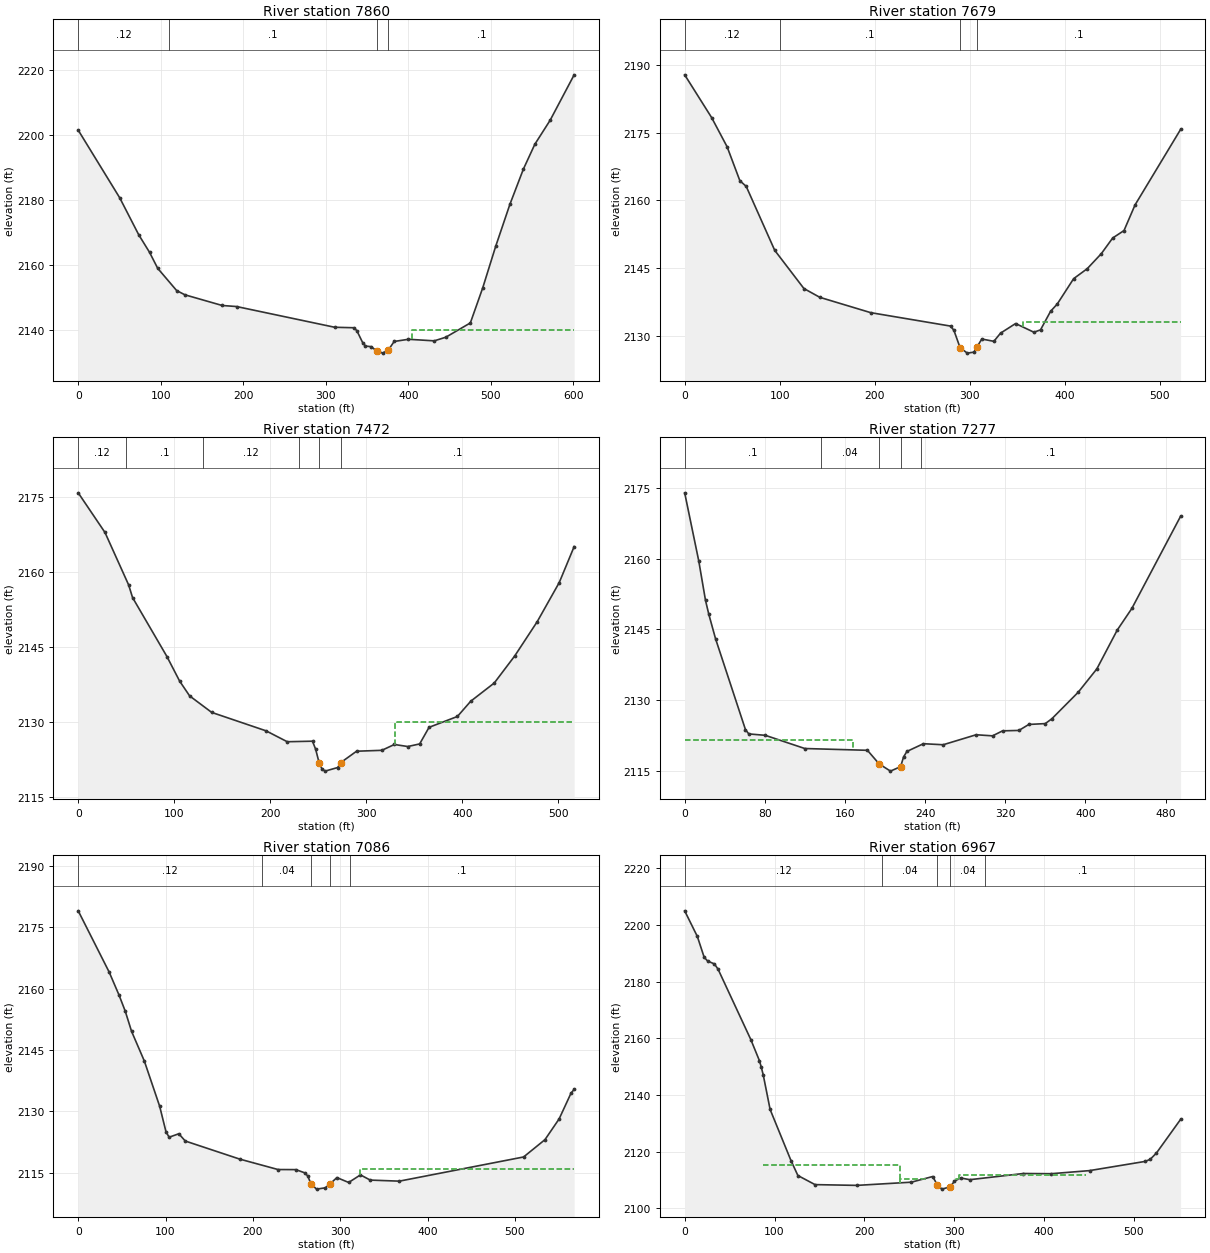
Type RM Length L Ch R = 1 ,7860    ,181.2,181.5,181.9
XS GIS Cut Line= 4
1952553.86191938211767.2620059311952428.31689807211773.098908721
1952089.33866105211655.512931522 1951973.1177143211647.606427394
#Sta/Elev= 30
       0 2201.46    50.3 2180.64    73.3 2169.28    86.5 2163.84    96.3 2158.95
   119.3 2152.09   129.3 2150.79   174.5  2147.5   191.9 2147.18   310.8  2140.8
   334.2 2140.65   337.7 2139.73   344.7 2136.08   348.1 2135.01   355.1 2134.83
   361.7 2133.49     369 2132.84   375.9 2133.83   382.9 2136.43   400.2  2137.1
   431.5 2136.62   445.4 2137.73   475.2 2142.13   490.2 2152.92   505.9  2165.7
   523.1 2178.61   539.5 2189.49   553.4 2197.14   571.9 2204.51     601 2218.49
#Mann= 4 ,-1 , 0
       0     .12       0     110      .1       0   361.7    .045       0
   375.9      .1       0
#XS Ineff= 2 , 0
                          404.23         2139.85
Permanent Ineff=
       F       F
Bank Sta=361.7,375.9
XS Rating Curve= 0 ,0
Exp/Cntr=0.3,0.1

Type RM Length L Ch R = 1 ,7679    ,211.6,206.8,201.2
XS GIS Cut Line= 4
1952550.55401955211564.9666727811952435.81547377211589.361403952
1952135.18625441211475.3973861581952052.36699231 211484.30139598
#Sta/Elev= 30
       0 2187.86    28.4 2178.36    44.7 2171.88    58.1 2164.36    64.8  2163.1
    94.8 2148.91   125.5 2140.44   142.3 2138.48   195.9 2135.08   279.9  2132.1
   283.4 2131.17   289.9 2127.33   297.5  2126.1   304.5 2126.32   307.7 2127.47
   312.8 2129.23   325.5 2128.72   332.5 2130.53   348.4 2132.67   367.6 2130.74
   374.6 2131.26   385.2 2135.38   392.2 2136.99   409.5 2142.63   423.8 2144.84
   438.6 2148.17   450.6 2151.65   462.5  2153.3   474.1 2158.98   522.1 2175.75
#Mann= 4 ,-1 , 0
       0     .12       0     100      .1       0   289.9    .045       0
   307.7      .1       0
#XS Ineff= 2 , 0
                          356.28         2133.02
Permanent Ineff=
       F       F
Bank Sta=289.9,307.7
XS Rating Curve= 0 ,0
Exp/Cntr=0.3,0.1

Type RM Length L Ch R = 1 ,7472    ,195.6,195,192.6
XS GIS Cut Line= 4
1952532.48979844211419.8869549651952466.71005811 211331.45331239
1952149.59549804211324.1003280521952062.27906107211342.010865444
#Sta/Elev= 30
       0 2175.92    27.9 2167.97    52.5 2157.47    56.6 2154.93    92.4 2143.11
   105.6  2138.2     116 2135.23     139 2131.92   195.7 2128.22   217.7 2126.04
     244 2126.15   247.3 2124.52   250.9 2121.82   253.8 2120.63   257.1 2120.15
   270.2 2120.87   273.5 2121.87   289.9 2124.14   316.2 2124.32   329.3 2125.49
   343.2 2125.08   355.6  2125.6   365.4 2128.93   394.9  2131.1   408.8 2134.16
   433.3 2137.81   454.6 2143.23     478 2150.09     501 2157.95   516.5 2165.15
#Mann= 6 ,-1 , 0
       0     .12       0      50      .1       0  130.22     .12       0
  230.22      .1       0   250.9    .045       0   273.5      .1       0
#XS Ineff= 2 , 0
                             330            2130
Permanent Ineff=
       F       F
Bank Sta=250.9,273.5
XS Rating Curve= 0 ,0
Exp/Cntr=0.3,0.1

Type RM Length L Ch R = 1 ,7277    ,194.1,190.4,188.3
XS GIS Cut Line= 4
1952484.63569233  211137.74959041952429.92078319211127.610642199
1952080.82410799211150.534438882 1952000.6731239211190.369693541
#Sta/Elev= 30
       0    2174    14.1 2159.49    20.8 2151.15    24.1  2148.2    30.8 2143.03
    60.7 2123.71      64 2122.82    80.5 2122.52   119.9 2119.72   182.4 2119.34
   193.9  2116.5   193.9 2116.48   205.4 2114.92   215.5 2115.87   218.5 2117.94
   221.8  2119.1   238.3 2120.74     258 2120.52   290.9 2122.64   307.3 2122.41
   317.3 2123.47   333.6 2123.56   343.5 2124.83   359.9 2125.01   366.4 2126.02
   392.8 2131.67   411.4 2136.63   431.7 2144.85   446.3 2149.45     495 2169.03
#Mann= 5 ,-1 , 0
       0      .1       0  135.65     .04       0   193.9    .045       0
   215.5     .04       0  235.65      .1       0
#XS Ineff= 2 , 0
          167.89 2121.43
Permanent Ineff=
       F       F
Bank Sta=193.9,215.5
XS Rating Curve= 0 ,0
Exp/Cntr=0.3,0.1

Type RM Length L Ch R = 1 ,7086    ,134.6,119.3,107.4
XS GIS Cut Line= 3
1952471.42505373210783.7771240631952414.78966248210912.873842638
1952001.32199883211019.373322242
#Sta/Elev= 30
       0    2179    35.5    2164    46.8 2158.37    53.9 2154.44    61.1 2149.53
    75.7 2142.29    93.3  2131.2   100.5 2124.99   104.1 2123.65   115.2  2124.5
   122.6 2122.72   184.8 2118.31   228.8 2115.75   249.2 2115.73   259.3 2114.95
   262.7 2114.21   266.6 2112.26   272.9 2110.96     283 2111.28   288.2 2112.21
   296.2 2113.78   309.7 2112.59   323.2 2114.44   334.4 2113.17   367.7 2112.91
     510 2118.82   534.5 2123.06   550.7 2128.13   564.2 2134.37   567.9 2135.36
#Mann= 5 ,-1 , 0
       0     .12       0  210.97     .04       0   266.6    .045       0
   288.2     .04       0  310.97      .1       0
#XS Ineff= 2 , 0
                          323.15         2115.98
Permanent Ineff=
       F       F
Bank Sta=266.6,288.2
XS Rating Curve= 0 ,0
Exp/Cntr=0.5,0.3

Type RM Length L Ch R = 1 ,6967    ,55.2,54.7,55
XS GIS Cut Line= 4
1952440.02821428 210687.881036571952224.47511426210821.794281117
1952192.32018135210922.3798510251952008.72926863 210980.87325921
#Sta/Elev= 30
       0 2204.93    14.1 2195.88    21.7 2188.54    25.6 2187.21    33.1  2186.2
    37.2 2184.32    73.6 2159.53    83.2 2152.07    85.1 2149.96    87.4 2147.13
    95.1 2134.86   118.3 2116.86     126 2111.57   145.1 2108.36   191.7 2108.09
   252.3 2109.22     276 2111.21   281.32108.248   286.4 2106.77   295.72107.617
   300.1 2109.51     307 2110.72   317.4  2110.1     377 2112.28     408 2112.21
   450.6  2113.3   512.6 2116.55   518.2 2117.29   525.1 2119.51     552 2131.38
#Mann= 5 ,-1 , 0
       0     .12       0     220     .04       0   281.3    .045       0
   295.7     .04       0  333.76      .1       0
#XS Ineff= 4 ,-1
   86.71  239.24 2115.35     240     270 2110.36     302     305 2110.36
     305   446.6 2111.75
Permanent Ineff=
       F       F       F       F
Bank Sta=281.3,295.7
XS Rating Curve= 0 ,0
Exp/Cntr(USF)=0,0
Exp/Cntr=0.5,0.3