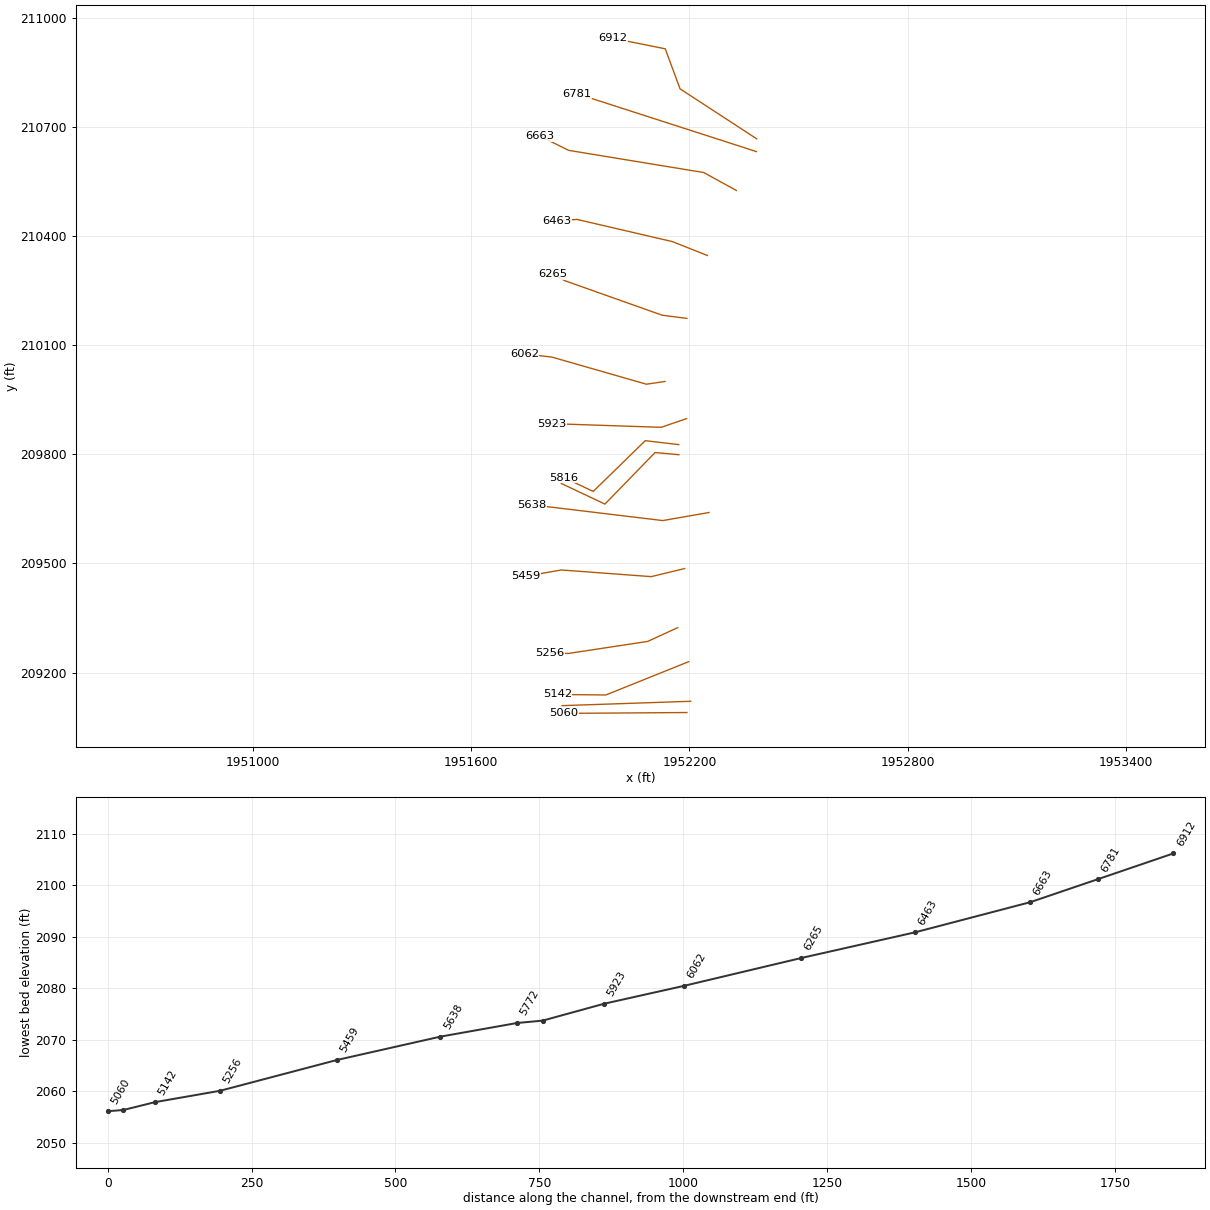
HEC-RAS study NFKMTNCK.prj: NFKMTNCK

--- NFKMTNCK.g01 (geometry) --- (continued)

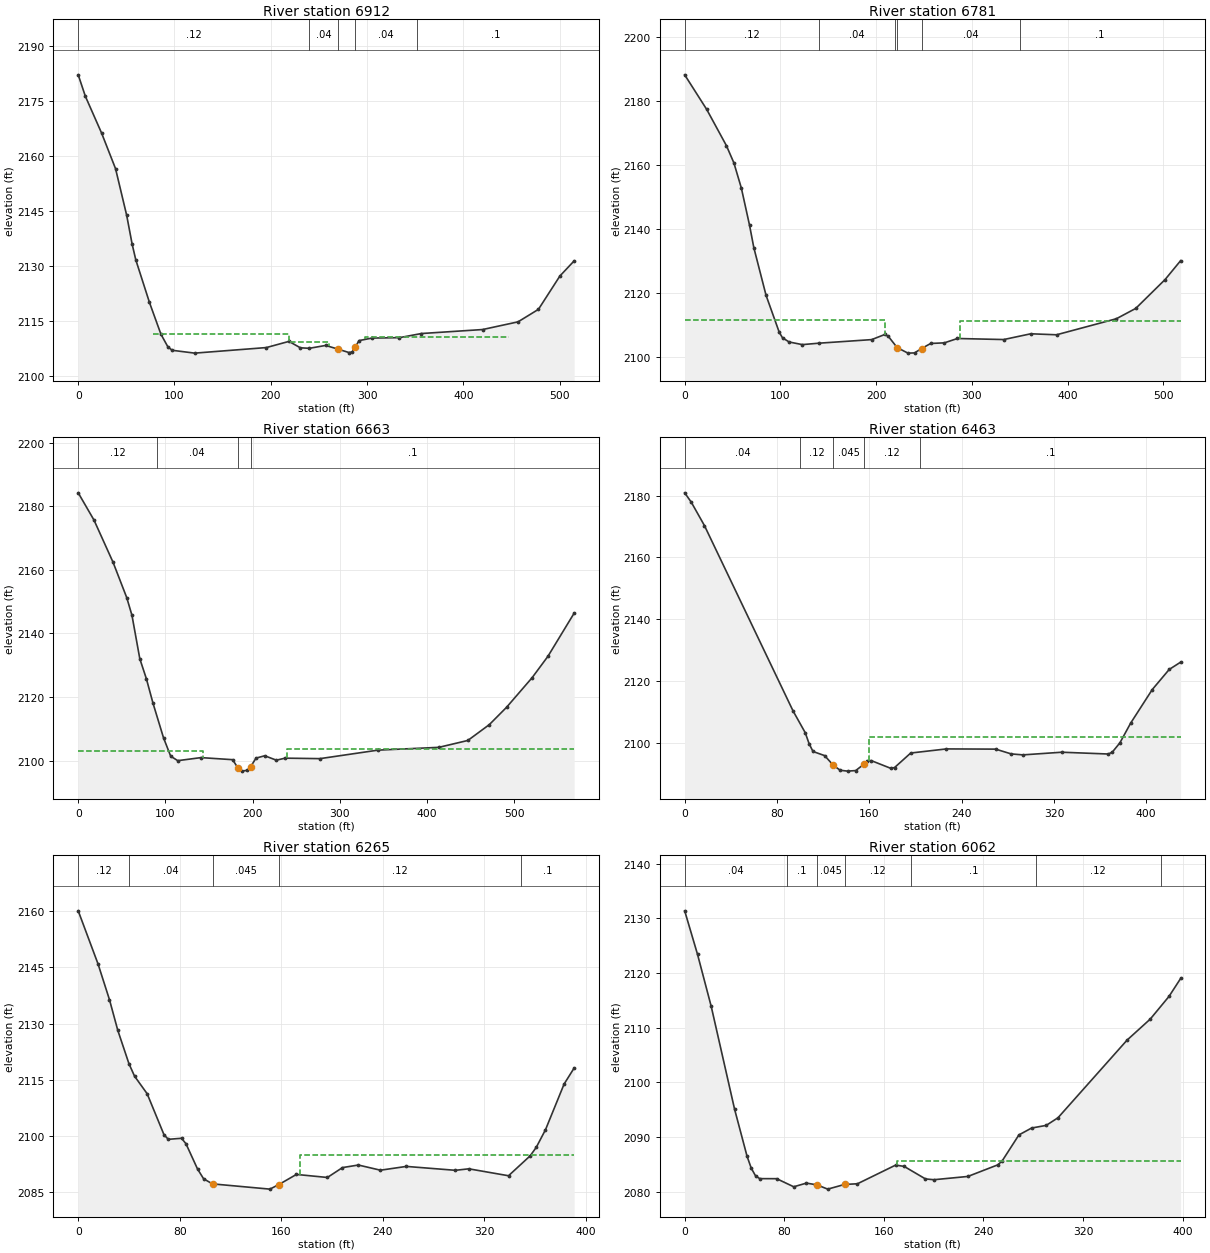
Type RM Length L Ch R = 1 ,6912    ,118.5,131.7,140.1
XS GIS Cut Line= 4
1952385.14438949210668.0286883411952174.41119684210805.453484345
1952133.60564206210915.5727215941951990.40824677210944.362790523
#Sta/Elev= 30
       0 2182.24     7.4 2176.39    24.3  2166.3    38.8 2156.56    50.3 2143.87
      56 2135.96    59.8 2131.65      74    2120    85.9 2111.32      93 2107.92
    97.5 2106.92     121 2106.14   195.4 2107.66   218.9 2109.35   230.7  2107.6
     240 2107.46     257 2108.24   269.42107.269   281.1 2106.31   284.6 2106.45
   287.6 2107.69   291.6 2109.56   305.1 2110.26   333.6 2110.37   356.5  2111.5
     420 2112.59   456.8 2114.69     478 2118.11   500.3 2127.23   515.1 2131.37
#Mann= 5 ,-1 , 0
       0     .12       0     240     .04       0   269.4    .045       0
   287.6     .04       0  351.58      .1       0
#XS Ineff= 4 ,-1
   77.22  218.99 2111.42     220   260.1  2109.2     293   297.7  2109.2
   297.7   447.9  2110.5
Permanent Ineff=
       F       F       F       F
Bank Sta=269.4,287.6
XS Rating Curve= 0 ,0
Exp/Cntr(USF)=0,0
Exp/Cntr=0.5,0.3

Type RM Length L Ch R = 1 ,6781    ,112.9,117.2,119.4
XS GIS Cut Line= 2
1952384.36386468210632.8814882191951891.39051897 210791.86539221
#Sta/Elev= 30
       0 2188.04      23 2177.24    43.6 2165.92    51.4 2160.54    59.2 2152.67
    67.8 2140.99    72.2 2134.09      85 2119.17    98.8 2107.61   102.2  2105.9
   109.1  2104.6   122.9 2103.78     140 2104.22   195.3 2105.34   209.1 2106.95
   212.6  2106.4   221.9 2102.86   233.2 2101.12   240.1 2101.19   247.4 2102.56
     257 2104.14   271.2 2104.33   284.9 2105.69   333.2 2105.36   361.5 2107.16
   388.4 2106.85   450.9 2111.86   471.1 2115.08   501.8 2124.11     518    2130
#Mann= 6 ,-1 , 0
       0     .12       0     140     .04       0     220     .12       0
   221.9    .045       0   247.4     .04       0     350      .1       0
#XS Ineff= 2 , 0
          208.86 2111.42  287.97         2111.22
Permanent Ineff=
       F       F
Bank Sta=221.9,247.4
XS Rating Curve= 0 ,0
Exp/Cntr(USF)=0,0
Exp/Cntr=0.3,0.1

Type RM Length L Ch R = 1 ,6663    ,201.2,200.1,199.2
XS GIS Cut Line= 4
1952329.23782689210525.9409656191952239.54255568210575.298770929
1951868.17704942210636.2105735431951787.76162775210675.937934205
#Sta/Elev= 30
       0  2184.2    18.1 2175.62    39.9 2162.38    55.6 2151.25    61.6 2145.68
    70.6 2132.01    78.1 2125.75    85.7 2118.05    97.8 2107.12     106 2101.36
   114.1 2099.96   140.7 2100.92     177 2100.27   182.7 2097.81   187.2 2096.67
   193.9 2096.93   197.5 2098.01   203.8 2100.77   213.8  2101.5   227.1 2100.11
   237.1 2100.75   277.1  2100.6   343.5 2103.27   413.3 2104.15   446.5 2106.31
   471.2  2111.3   490.9 2116.74   520.2 2126.05   538.4  2132.8   568.4 2146.36
#Mann= 4 ,-1 , 0
       0     .12       0      90     .04       0   182.7    .045       0
   197.5      .1       0
#XS Ineff= 2 , 0
          143.32 2102.91  239.66         2103.52
Permanent Ineff=
       F       F
Bank Sta=182.7,197.5
XS Rating Curve= 0 ,0
Exp/Cntr=0.3,0.1

Type RM Length L Ch R = 1 ,6463    ,201.3,197.9,194.5
XS GIS Cut Line= 4
1952249.66768344210347.070558985 1952153.0870939210385.358741272
 1951891.1008461210446.2705438871951834.21557085210443.181303493
#Sta/Elev= 30
       0  2180.9     5.7 2177.88    17.1 2170.32    93.9 2110.32   104.5 2103.24
   107.8 2099.73   111.2 2097.18   121.3 2095.84   128.8 2092.72   134.8  2091.1
   141.2 2090.82   148.2    2091   155.1 2092.98   158.3 2094.15   161.7 2094.22
   178.6 2091.73   181.9 2091.98   195.9 2096.68   226.9 2098.01   269.5 2097.94
     283 2096.39   293.1 2096.08   326.8 2096.94   367.2 2096.36   370.6 2096.97
   377.2 2099.99   386.5 2106.36   405.2 2117.21   419.9 2123.73   429.8 2126.09
#Mann= 5 ,-1 , 0
       0     .04       0     100     .12       0   128.8    .045       0
   155.1     .12       0  203.89      .1       0
#XS Ineff= 2 , 0
                             160            2102
Permanent Ineff=
       F       F
Bank Sta=128.8,155.1
XS Rating Curve= 0 ,0
Exp/Cntr=0.3,0.1

Type RM Length L Ch R = 1 ,6265    ,199.7,203.2,206.8
XS GIS Cut Line= 4
1952193.29827853210174.0760854231952125.33124269 210182.83934799
1951857.41755603210277.802813163 1951824.0721582210295.953484186
#Sta/Elev= 30
       0 2160.09    15.6 2145.93    24.6 2136.41    31.2 2128.18      40 2119.27
    44.4 2115.96    54.3 2111.29    67.6 2100.33      71 2099.12    81.4  2099.4
    84.9 2097.94      94  2091.2    98.8 2088.58   105.8 2087.23     151 2085.83
     158 2087.04   171.9 2089.75   196.3 2088.94   208.2 2091.58   220.7 2092.26
   238.1 2090.88   258.5 2091.89   297.2 2090.85   307.7 2091.25     339  2089.4
     356  2094.7   360.8 2096.95   368.1 2101.66   382.8 2113.88   390.7 2118.15
#Mann= 5 ,-1 , 0
       0     .12       0      40     .04       0   105.8    .045       0
     158     .12       0  348.53      .1       0
#XS Ineff= 2 , 0
                             175            2095
Permanent Ineff=
       F       F
Bank Sta=105.8,158
XS Rating Curve= 0 ,0
Exp/Cntr=0.3,0.1

Type RM Length L Ch R = 1 ,6062    ,135.2,139.5,143.2
XS GIS Cut Line= 4
 1952133.1966836210000.697338599  1952081.833983209993.094994059
1951821.87257186 210067.716041051951746.27731643210076.069484186
#Sta/Elev= 30
       0 2131.36    10.3 2123.41    21.3 2113.89    40.1 2095.05    50.1 2086.46
    53.5 2084.26    56.9 2082.88    60.3 2082.36    73.9 2082.35    87.6 2080.87
    97.8 2081.54   106.3 2081.22   114.9 2080.44   128.5  2081.3   138.8 2081.42
   169.5 2084.84   176.3  2084.6   193.4 2082.31   200.2 2082.16   227.5 2082.76
   251.4 2084.87   254.9 2085.55   268.5 2090.36   278.7 2091.62   290.4  2092.1
   299.9  2093.5   355.4 2107.71     374 2111.55   389.1 2115.71   398.4 2118.98
#Mann= 7 ,-1 , 0
       0     .04       0   81.92      .1       0   106.3    .045       0
   128.5     .12       0  181.92      .1       0  281.92     .12       0
  382.38      .1       0
#XS Ineff= 2 , 0
                          170.59         2085.58
Permanent Ineff=
       F       F
Bank Sta=106.3,128.5
XS Rating Curve= 0 ,0
Exp/Cntr=0.3,0.1

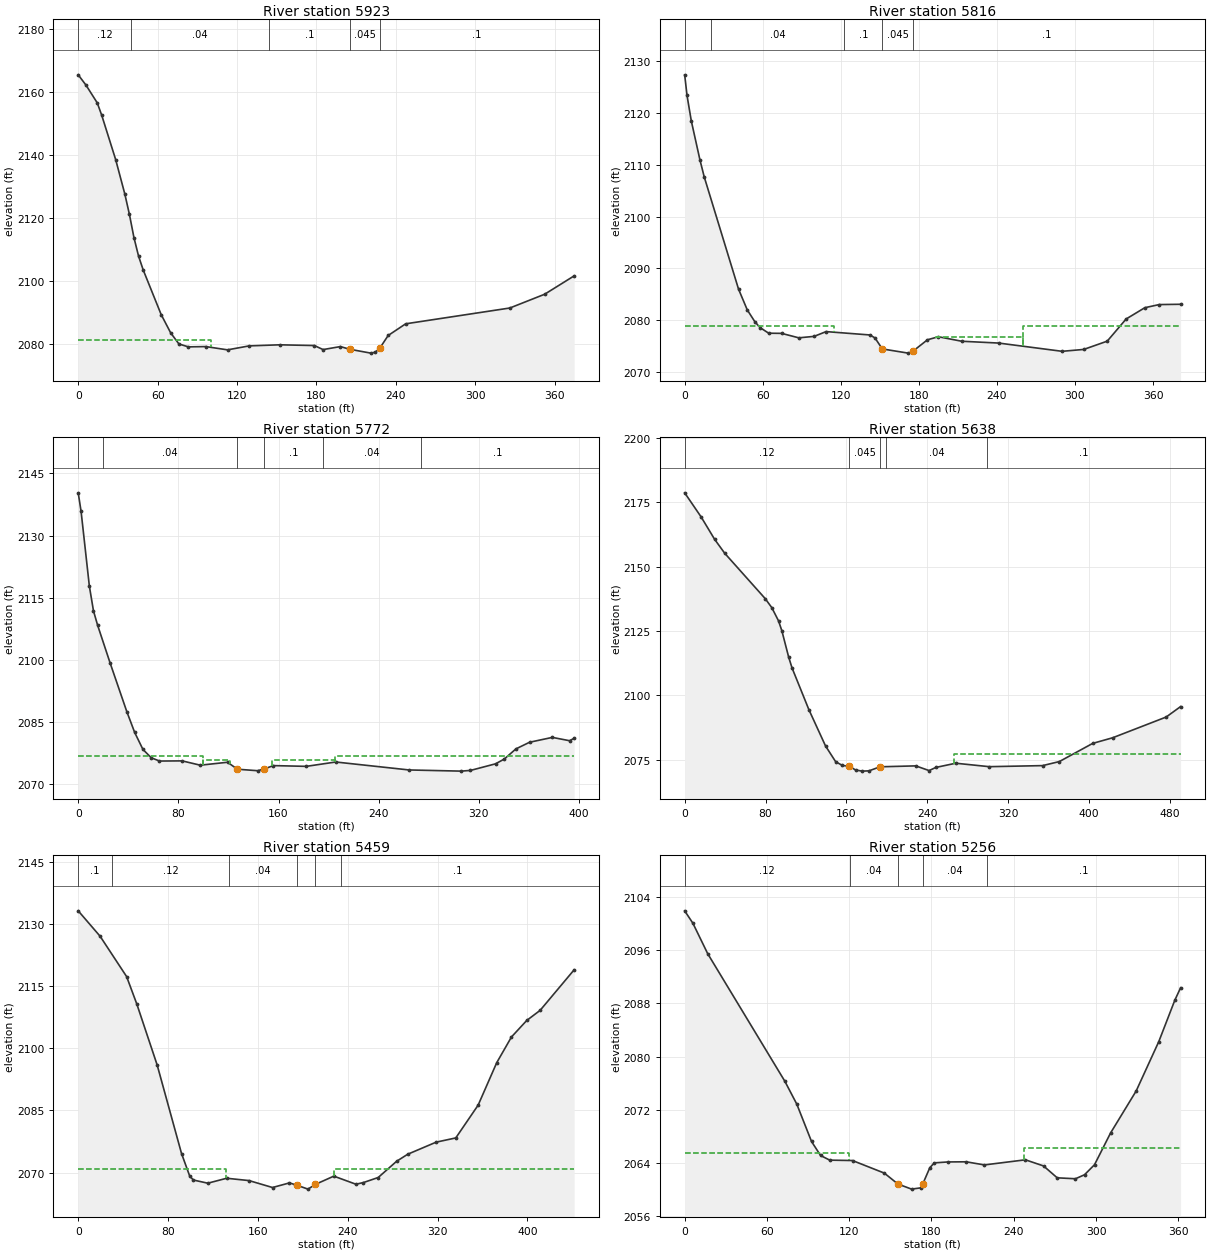
Type RM Length L Ch R = 1 ,5923    ,92.1,106.5,118.5
XS GIS Cut Line= 3
1952192.39303027 209898.512166081952122.39116286209874.533625863
1951821.88590886209884.589142728
#Sta/Elev= 30
       0 2165.34     5.9 2162.06    14.4 2156.42    17.8 2152.45    28.3 2138.42
    35.2 2127.51    38.7 2120.99    42.1 2113.66    45.6 2107.75    49.1 2103.37
    62.7 2089.17    69.9 2083.36    76.1 2079.86    83.2 2078.94    96.4 2079.03
   112.8 2077.99   129.2 2079.25   152.2 2079.59   178.4 2079.36     185 2078.08
   198.1 2079.03   205.2 2078.17   221.1 2076.95   224.4 2077.24   227.7 2078.43
   234.2 2082.56   247.4 2086.26   326.1 2091.28   352.4 2095.65   374.7 2101.49
#Mann= 5 ,-1 , 0
       0     .12       0      40     .04       0  143.99      .1       0
   205.2    .045       0   227.7      .1       0
#XS Ineff= 2 , 0
             100    2081
Permanent Ineff=
       F       F
Bank Sta=205.2,227.7
XS Rating Curve= 0 ,0
Exp/Cntr(USF)=0,0
Exp/Cntr=0.5,0.3

Type RM Length L Ch R = 1 ,5816    ,44,44.4,44.6
XS GIS Cut Line= 4
1952170.73499395209826.9632960781952078.68833957 209837.79231424
1951935.59059956209698.1753300731951855.53321529209736.076893642
#Sta/Elev= 30
       0 2127.34     1.8 2123.36     5.1 2118.44    11.7 2110.97      15 2107.68
    41.4 2086.02    48.1 2082.02    53.9 2079.75      58 2078.59    64.6 2077.52
    74.5 2077.49    87.7 2076.63    99.5 2076.91   108.7 2077.83   142.5 2077.18
   146.3  2076.6   151.9 2074.49   171.8 2073.68   175.4 2074.04   186.6 2076.25
     195 2076.84     213 2075.97   241.4 2075.62   290.1 2074.03   306.7 2074.39
   324.8 2075.99   339.3 2080.26   353.7 2082.44   364.7 2083.04   381.2  2083.1
#Mann= 5 ,-1 , 0
       0     .12       0      20     .04       0  122.68      .1       0
   151.9    .045       0   175.4      .1       0
#XS Ineff= 4 ,-1
       0     115    2079     115     145  2076.7   192.8     260  2076.7
     260 381.182    2079
Permanent Ineff=
       F       F       F       F
Bank Sta=151.9,175.4
XS Rating Curve= 0 ,0
Exp/Cntr(USF)=0,0
Exp/Cntr=0.5,0.3

Type RM Length L Ch R = 1 ,5772    ,150.6,133.3,120.3
XS GIS Cut Line= 4
1952171.25066148209799.1602216681952105.71791268209805.219315164
1951967.77684799209663.3677716941951848.05603608209719.962283281
#Sta/Elev= 30
       0 2140.29     2.3 2135.81     8.9 2117.81    12.2 2111.83    15.5 2108.38
    25.4 2099.35    38.8 2087.57    45.1 2082.54    51.7 2078.45    58.3 2076.45
    64.9 2075.65      83 2075.69    97.5 2074.65   119.3 2075.36   127.1 2073.68
   143.3 2073.32     148 2073.69   155.9 2074.55   182.2 2074.37   205.7 2075.42
   264.3  2073.5   305.9 2073.22   313.3 2073.39   333.3 2074.98   340.3 2076.13
   349.6 2078.58   360.5 2080.18   378.7 2081.35   392.4 2080.55   396.1 2081.13
#Mann= 6 ,-1 , 0
       0     .12       0      20     .04       0   127.1    .045       0
     148      .1       0  195.81     .04       0  273.67      .1       0
#XS Ineff= 4 ,-1
       0     100  2076.8     100     121  2075.8     155     205  2075.8
     205 396.098  2076.8
Permanent Ineff=
       F       F       F       F
Bank Sta=127.1,148
XS Rating Curve= 0 ,0
Exp/Cntr(USF)=0,0
Exp/Cntr=0.5,0.3

Type RM Length L Ch R = 1 ,5638    ,183.6,179.7,178.5
XS GIS Cut Line= 3
1952253.90661882209640.2394551821952126.78608061209618.048350235
1951767.58589951  209661.3061441
#Sta/Elev= 30
       0 2178.71    16.3 2169.33    29.6 2160.66    39.6 2155.24    79.6 2137.64
    86.2 2134.11    92.9 2128.94    96.2 2125.07   102.9 2114.89   106.2 2110.72
   122.9 2094.47   139.4 2080.35   149.4 2074.23     156 2072.79   163.12072.437
   169.2 2070.99   175.8 2070.57   182.4 2070.68   193.32072.251   228.7 2072.61
   241.9 2070.78   248.5    2072   268.3 2073.64   301.4  2072.3   354.2 2072.71
   370.8 2074.29   403.8 2081.35   423.6 2083.54   476.5 2091.59   490.8 2095.66
#Mann= 5 ,-1 , 0
       0     .12       0   163.1    .045       0   193.3     .12       0
  199.04     .04       0  299.04      .1       0
#XS Ineff= 2 , 0
                           266.2         2077.04
Permanent Ineff=
       F       F
Bank Sta=163.1,193.3
XS Rating Curve= 0 ,0
Exp/Cntr=0.3,0.1

Type RM Length L Ch R = 1 ,5459    ,199.2,203.2,205.3
XS GIS Cut Line= 4
1952186.83573341209486.0349483281952095.11053611209463.848803288
1951847.81924267209482.2036291521951750.06570229209464.931421608
#Sta/Elev= 30
       0 2133.12    19.5 2126.99    43.1 2117.27    52.2 2110.64    70.3 2095.96
      92 2074.62    99.3 2069.17   102.6 2068.23   115.4 2067.47   132.2 2068.66
   152.1  2068.1     173 2066.43   188.1 2067.54     195 2066.96   204.6 2066.04
   211.1 2067.17   227.6 2069.17   247.3 2067.22   253.9 2067.62   267.1 2068.84
   283.5 2072.75   293.4 2074.45   318.7 2077.36   336.2 2078.38   356.1 2086.28
   372.7 2096.54   385.8 2102.72   399.4  2106.7   411.3 2109.13   441.6 2118.91
#Mann= 6 ,-1 , 0
       0      .1       0      30     .12       0  134.37     .04       0
     195    .045       0   211.1     .04       0  234.37      .1       0
#XS Ineff= 2 , 0
          131.83 2070.95  227.61         2070.85
Permanent Ineff=
       F       F
Bank Sta=195,211.1
XS Rating Curve= 0 ,0
Exp/Cntr=0.3,0.1

Type RM Length L Ch R = 1 ,5256    ,109.7,113.2,115.8
XS GIS Cut Line= 4
1952167.84694656209323.5320093951952085.54750457  209285.7139433
 1951867.2256314 209252.561362561951816.95187787209254.160175573
#Sta/Elev= 30
       0 2101.92       6 2100.05    16.8 2095.47    73.1 2076.27    81.8 2072.83
    92.5 2067.23    99.1 2065.12   105.8 2064.42   122.4 2064.36   145.6 2062.47
   155.5 2060.83   165.5 2060.06   172.1 2060.25   173.7 2060.86   178.8 2063.29
   182.1 2064.01   192.1 2064.15   205.3 2064.17   218.6  2063.7   248.5 2064.47
   261.7 2063.55   271.7 2061.76     285 2061.62   291.6 2062.22   298.9 2063.73
   310.6  2068.5   329.3 2074.83   345.8 2082.26   357.5 2088.49   361.7 2090.35
#Mann= 5 ,-1 , 0
       0     .12       0  120.57     .04       0   155.5    .045       0
   173.7     .04       0  220.57      .1       0
#XS Ineff= 2 , 0
             120  2065.5  247.26          2066.3
Permanent Ineff=
       F       F
Bank Sta=155.5,173.7
XS Rating Curve= 0 ,0
Exp/Cntr=0.3,0.1

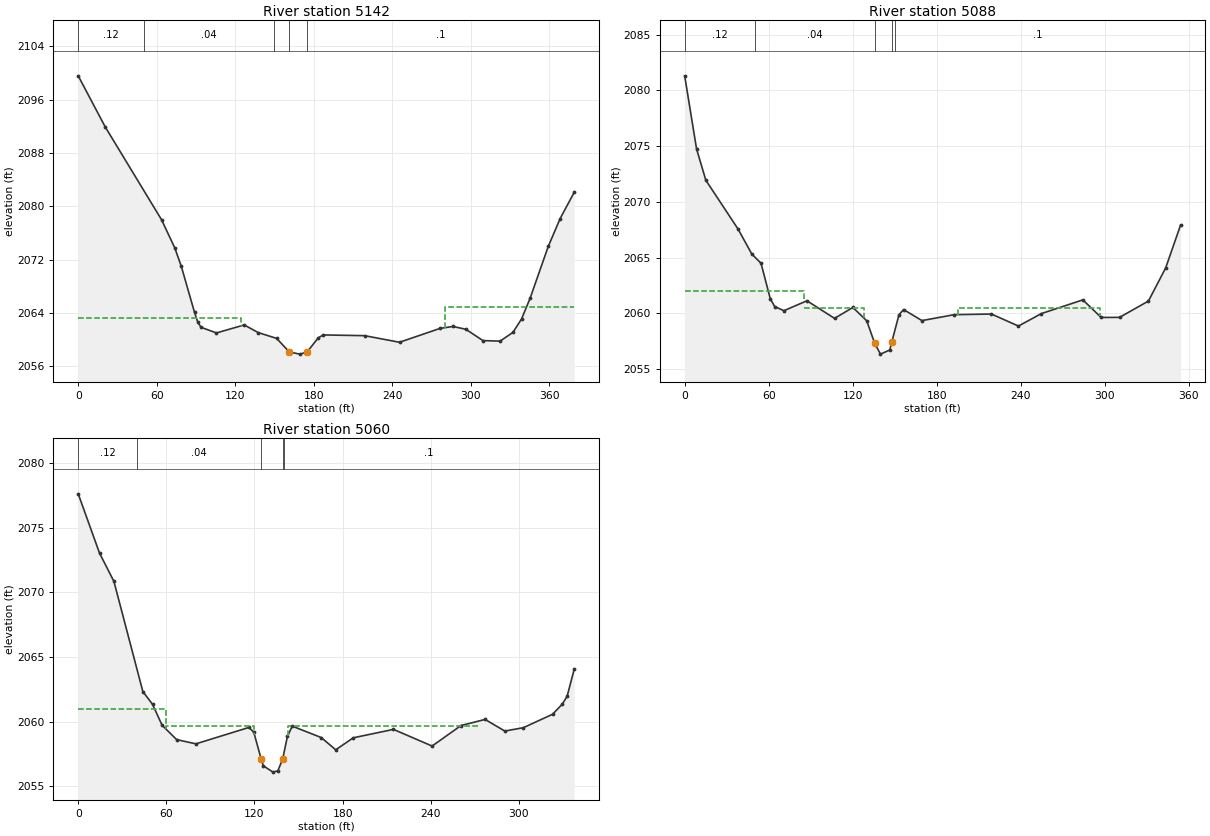
Type RM Length L Ch R = 1 ,5142    ,58.6,54.8,50.9
XS GIS Cut Line= 3
1952198.15152329209229.9490450371951970.39836352209138.418058187
1951836.75452826209139.707227016
#Sta/Elev= 30
       0  2099.6    20.6 2091.95    63.7 2078.01    73.8 2073.79    78.8 2071.02
    88.9 2064.12    91.4 2062.65    93.9 2061.87   105.7 2061.03   126.9 2062.23
   137.6 2061.08   151.7 2060.21   161.4 2058.17   169.4 2057.85   174.8 2058.14
   183.5 2060.29   187.3 2060.73   218.9 2060.62   245.6 2059.63   276.6 2061.71
   286.4    2062   296.3 2061.58   309.4 2059.88   322.5  2059.8   332.3 2061.11
   338.9 2063.12   345.5 2066.27   359.3    2074   368.4 2078.19   379.1 2082.11
#Mann= 5 ,-1 , 0
       0     .12       0      50     .04       0     150      .1       0
   161.4    .045       0   174.8      .1       0
#XS Ineff= 2 , 0
          124.62 2063.25  280.59         2064.86
Permanent Ineff=
       F       F
Bank Sta=161.4,174.8
XS Rating Curve= 0 ,0
Exp/Cntr(USF)=0,0
Exp/Cntr=0.5,0.3

Type RM Length L Ch R = 1 ,5088    ,27.5,27.3,27.1
XS GIS Cut Line= 2
1952203.72239159209121.0336536091951849.84554806  209109.0443835
#Sta/Elev= 30
       0 2081.31     8.5 2074.74    15.1 2071.94    38.1 2067.56    47.9 2065.32
    54.5 2064.49    61.1 2061.31    64.3 2060.59    70.9 2060.23    87.3 2061.12
     107 2059.54   120.1 2060.52     130 2059.32   135.7 2057.29   139.8 2056.33
   146.4  2056.7   147.92057.427     153 2059.86   156.3 2060.33   169.4 2059.34
   192.4 2059.87     219 2059.93   238.3 2058.85   254.7 2059.97   284.3  2061.2
   297.4 2059.62   310.5 2059.63   331.1 2061.09   343.4 2064.06   354.1 2067.92
#Mann= 5 ,-1 , 0
       0     .12       0      50     .04       0   135.7    .045       0
   147.9     .04       0     150      .1       0
#XS Ineff= 3 ,-1
       0      85    2062      85     128  2060.5  195.23  296.232060.452
Permanent Ineff=
       F       F       F
Bank Sta=135.7,147.9
XS Rating Curve= 0 ,0
Exp/Cntr(USF)=0,0
Exp/Cntr=0.5,0.3

Type RM Length L Ch R = 1 ,5060    ,65.1,64.1,65.3
XS GIS Cut Line= 2
1952193.28012407209090.0936017161951855.64680779209087.773097824
#Sta/Elev= 30
       0 2077.64    14.5 2073.05    24.3 2070.86      44 2062.33    50.6 2061.34
    57.1 2059.72      67 2058.61    80.1 2058.28   116.2 2059.55   119.5 2059.19
   124.6 2057.08     126 2056.58   132.6 2056.09   135.9 2056.19   139.2 2057.11
   142.4 2058.85   145.7 2059.65   165.4 2058.77   175.3 2057.82   187.3 2058.75
   214.6  2059.4   240.9 2058.11   260.6  2059.7     277 2060.17   290.4 2059.27
     303 2059.53   322.9 2060.57   329.5 2061.35   332.8 2061.96   337.6 2064.04
#Mann= 5 ,-1 , 0
       0     .12       0      40     .04       0   124.6    .045       0
   139.2     .04       0     140      .1       0
#XS Ineff= 3 ,-1
       0      60    2061      60     1202059.691   142.5  271.952059.683
Permanent Ineff=
       F       F       F
Bank Sta=124.6,139.2
XS Rating Curve= 0 ,0
Exp/Cntr(USF)=0,0
Exp/Cntr=0.5,0.3