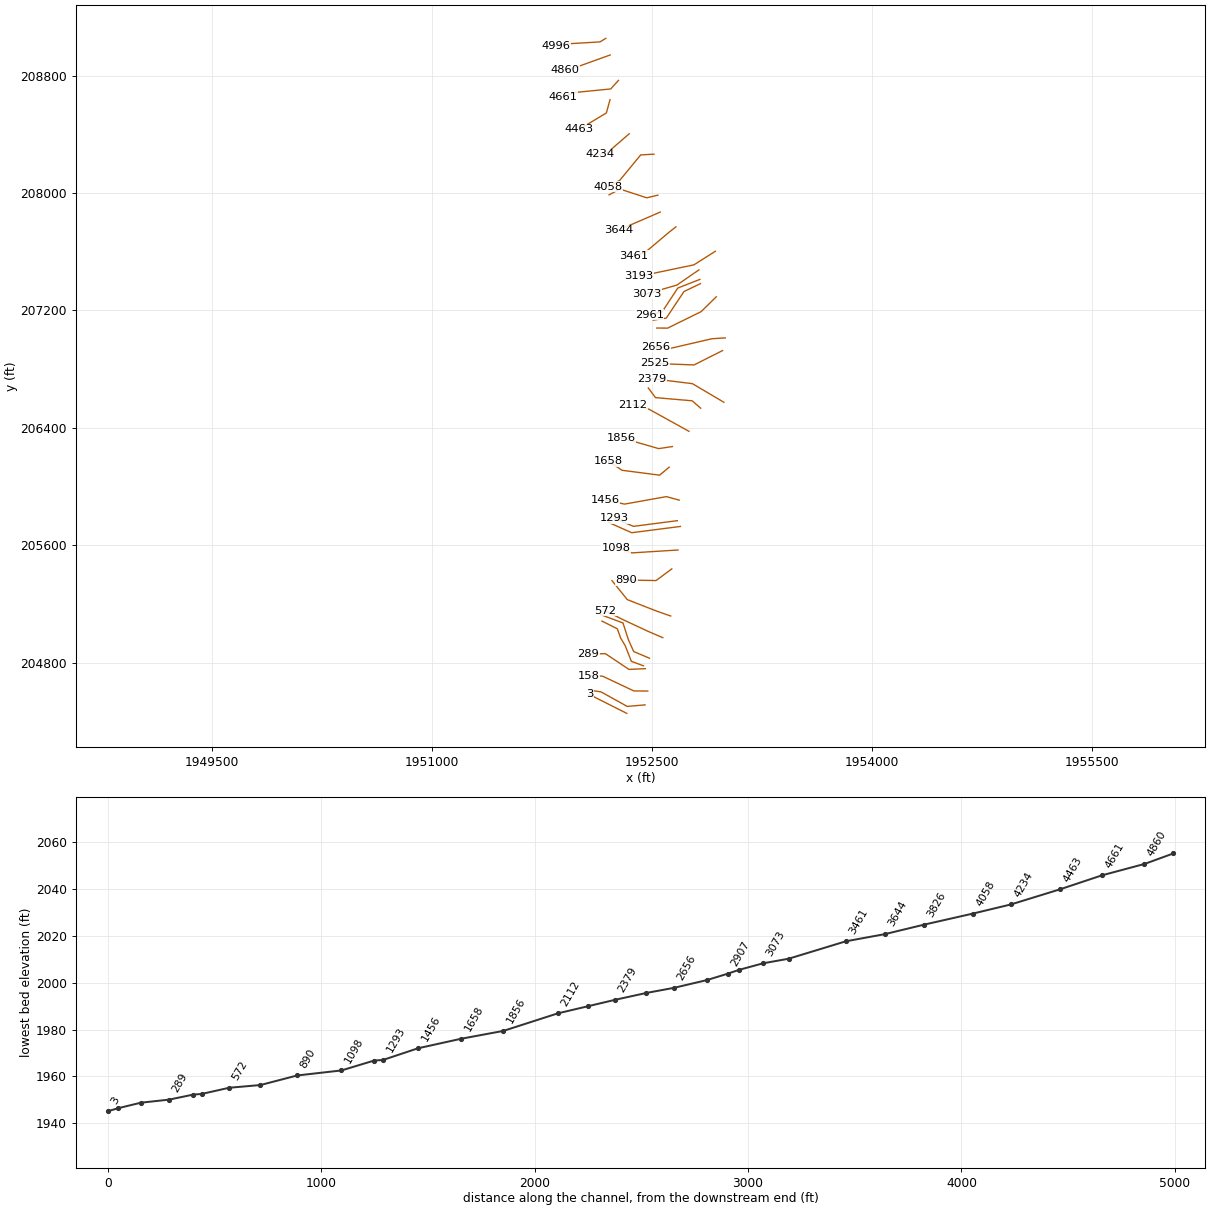
HEC-RAS study NFKMTNCK.prj: NFKMTNCK

--- NFKMTNCK.g01 (geometry) --- (continued)

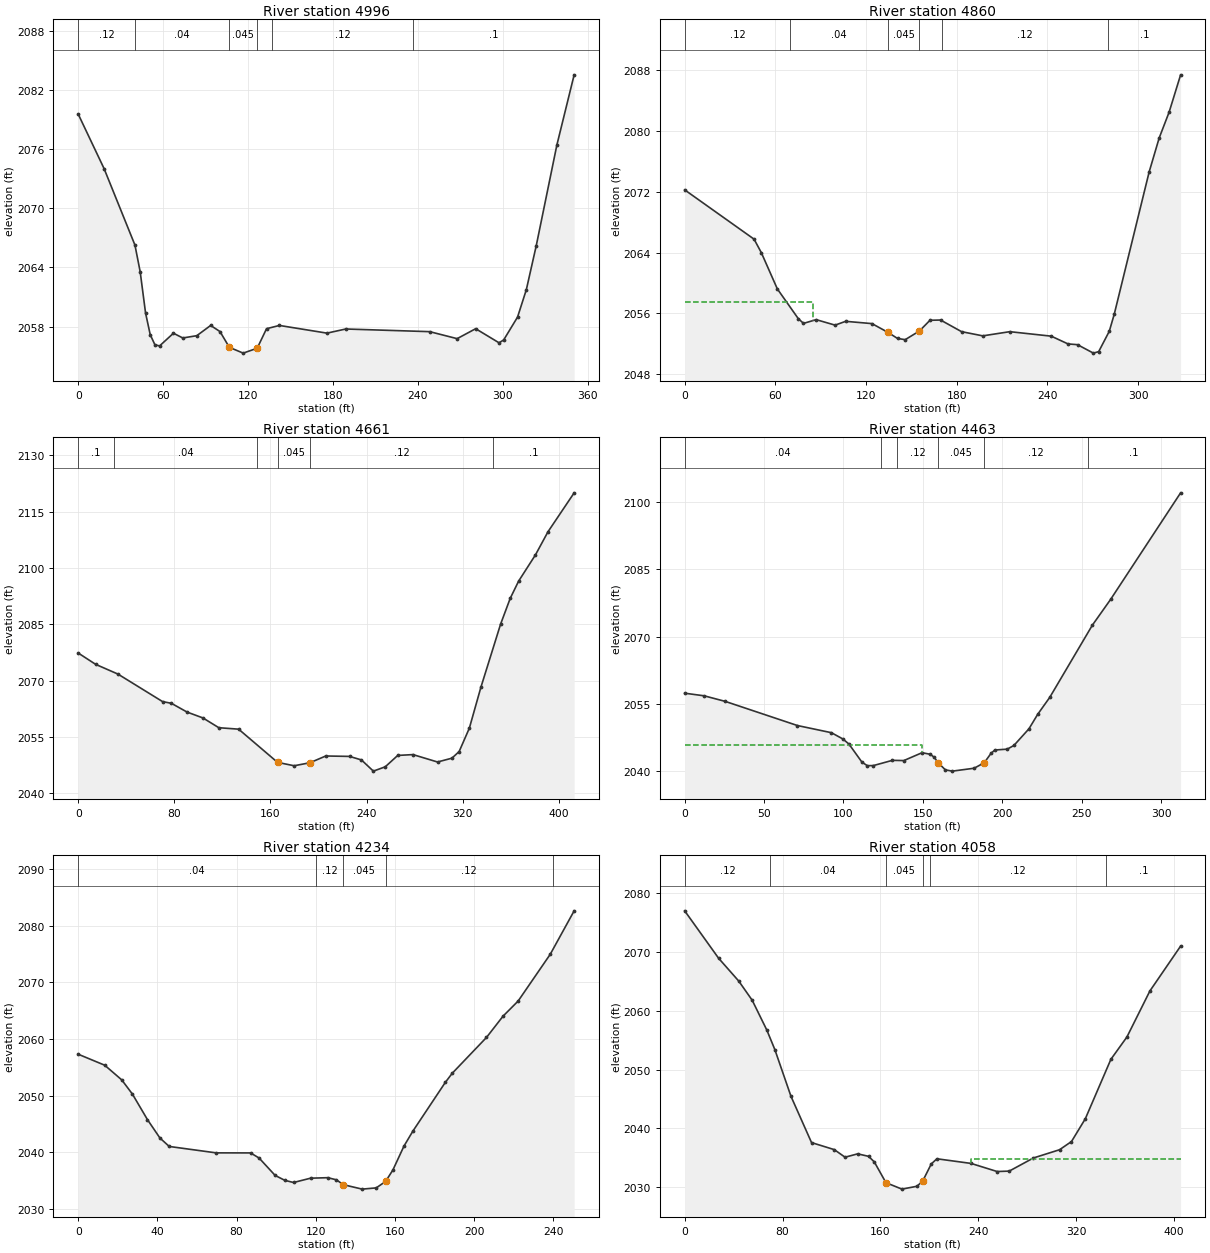
Type RM Length L Ch R = 1 ,4996    ,130.5,135.8,139.6
XS GIS Cut Line= 4
1952186.77575293 209054.622309911952146.66827825209030.271343143
  1951877.375234209014.5148352341951846.33968812209001.145677009
#Sta/Elev= 30
       0 2079.57    18.3 2074.03    40.1 2066.27    43.8 2063.56    47.6 2059.37
    50.9 2057.17    54.2 2056.15    57.5 2056.03    67.3 2057.32    73.9 2056.84
    83.8 2057.07    93.6 2058.11   100.2 2057.49   106.8 2055.89   116.6  2055.3
   126.5  2055.8   133.1 2057.78   142.2 2058.11   175.8 2057.33   189.1 2057.75
   248.4 2057.48   267.8 2056.77   280.9 2057.78   297.4 2056.35   300.7 2056.64
   310.5 2058.96   316.7 2061.74   323.7  2066.2   338.3 2076.44   350.5 2083.56
#Mann= 6 ,-1 , 0
       0     .12       0      40     .04       0   106.8    .045       0
   126.5     .04       0  136.92     .12       0  236.92      .1       0
Bank Sta=106.8,126.5
XS Rating Curve= 0 ,0
Exp/Cntr(USF)=0,0
Exp/Cntr=0.3,0.1

Type RM Length L Ch R = 1 ,4860    ,203,198.9,195.1
XS GIS Cut Line= 3
1952216.64529659208941.3651922691951952.12164764 208846.03144444
1951905.53460482208840.860394652
#Sta/Elev= 30
       0 2072.25    45.9 2065.77    50.7    2064    61.3 2059.23    75.1 2055.34
    78.6  2054.7      87 2055.19    99.5 2054.47   106.5 2054.97   123.9 2054.67
   134.4 2053.53   140.8 2052.72   145.9 2052.56   155.3  2053.7   162.3 2055.11
   169.3 2055.14   183.2 2053.61   197.2 2053.06   215.1 2053.61   242.5 2053.02
   253.6    2052   259.9  2051.9   270.4 2050.79   273.9 2050.99   280.9 2053.66
   284.2 2055.91   307.3 2074.62   313.9 2079.06   320.5 2082.47   328.1 2087.37
#Mann= 6 ,-1 , 0
       0     .12       0      70     .04       0   134.4    .045       0
   155.3     .04       0     170     .12       0     280      .1       0
#XS Ineff= 2 , 0
           84.92 2057.48
Permanent Ineff=
       F       F
Bank Sta=134.4,155.3
XS Rating Curve= 0 ,0
Exp/Cntr=0.3,0.1

Type RM Length L Ch R = 1 ,4661    ,189.5,198.2,207.5
XS GIS Cut Line= 4
1952272.80065054208768.1395766481952220.40540297 208709.69025772
1951974.59680597 208685.522026361951892.59822219208655.881530942
#Sta/Elev= 30
       0 2077.38    14.5 2074.37    33.1 2071.77    70.2 2064.45    77.5    2064
    90.6 2061.66   103.8  2060.1     117  2057.5   133.5 2057.11   165.9 2048.27
   179.7 2047.37   192.8 2048.17     206 2049.97   225.8 2049.86   235.7 2048.92
   245.6 2045.94   255.5 2047.09   265.9 2050.12   278.6 2050.34     299 2048.37
     311 2049.39     317 2051.16   325.5 2057.39   335.1 2068.27   351.5 2085.08
   359.5 2091.94   366.5 2096.53   380.5 2103.51   390.9 2109.65   412.7 2120.03
#Mann= 6 ,-1 , 0
       0      .1       0      30     .04       0   148.5     .12       0
   165.9    .045       0   192.8     .12       0  345.49      .1       0
Bank Sta=165.9,192.8
XS Rating Curve= 0 ,0
Exp/Cntr=0.3,0.1

Type RM Length L Ch R = 1 ,4463    ,226.7,229,231.8
XS GIS Cut Line= 3
1952215.29370892208636.5943192661952190.42285962208546.153828488
1952003.19603019208433.454502087
#Sta/Elev= 30
       0 2057.34    12.3 2056.75    25.5 2055.51      71 2050.11    92.4 2048.51
    99.7 2047.09   103.5 2045.95   111.6 2041.94     115 2041.14   118.8 2041.16
   130.8 2042.33     138 2042.28   149.5 2044.04   154.7 2043.68   157.2 2042.99
   159.5 2041.84   164.2 2040.19   168.6 2039.92   182.3 2040.57   188.7 2041.81
   192.9 2043.89   195.3 2044.64   203.1 2044.83   207.3 2045.65   216.8 2049.38
   222.3 2052.62   229.9 2056.41   256.7 2072.53   268.2 2078.29   312.3 2102.12
#Mann= 6 ,-1 , 0
       0     .04       0   123.8      .1       0   133.8     .12       0
   159.5    .045       0   188.7     .12       0   253.8      .1       0
#XS Ineff= 2 , 0
          149.66 2045.78
Permanent Ineff=
       F       F
Bank Sta=159.5,188.7
XS Rating Curve= 0 ,0
Exp/Cntr=0.3,0.1

Type RM Length L Ch R = 1 ,4234    ,174.1,176.7,179.6
XS GIS Cut Line= 3
1952346.33332247208404.3624183851952202.80585952 208280.17248787
1952144.17638228208263.991848783
#Sta/Elev= 30
       0  2057.3    13.4 2055.36      22 2052.77    27.4 2050.26      35 2045.75
    41.3 2042.51      46 2041.02    69.7 2039.89    87.1 2039.88    91.4 2038.98
    99.5 2035.91   104.4 2035.04   108.8 2034.66   117.4 2035.42   126.1 2035.51
   130.5 2035.13   133.9 2034.28   143.5 2033.49   150.6 2033.71   155.3 2034.84
     159 2036.86   164.6 2041.08     169 2043.67   185.5 2052.33     189 2053.94
   206.3 2060.26   214.7 2064.03   222.3 2066.69   238.5 2074.93   250.6 2082.61
#Mann= 5 ,-1 , 0
       0     .04       0     120     .12       0   133.9    .045       0
   155.3     .12       0   239.8      .1       0
Bank Sta=133.9,155.3
XS Rating Curve= 0 ,0
Exp/Cntr=0.3,0.1

Type RM Length L Ch R = 1 ,4058    ,253.5,231.2,208.2
XS GIS Cut Line= 4
1952514.87364955208265.3039354871952424.26310848208260.095794589
1952282.10741141 208087.522493691952202.90072686208042.559631954
#Sta/Elev= 30
       0 2077.04    27.7 2068.97    44.2 2065.07    55.2  2061.8    67.2  2056.7
    73.7  2053.4    86.9 2045.43   103.7 2037.55   122.3 2036.35   131.1 2035.06
   141.4 2035.63   150.3 2035.21     155 2034.26  164.512030.722   177.6 2029.62
   189.9 2030.11   194.6 2031.01   201.6 2033.92   206.2 2034.79   234.1    2034
   255.4 2032.62   265.3 2032.69   285.1 2034.93   306.4 2036.33   316.2 2037.73
   327.5 2041.61   348.4 2051.74   361.5 2055.54   380.3 2063.39   405.4 2071.03
#Mann= 6 ,-1 , 0
       0     .12       0      70     .04       0  164.51    .045       0
   194.6     .04       0  200.76     .12       0  344.34      .1       0
#XS Ineff= 2 , 0
                          234.37         2034.77
Permanent Ineff=
       F       F
Bank Sta=164.51,194.6
XS Rating Curve= 0 ,0
Exp/Cntr=0.3,0.1

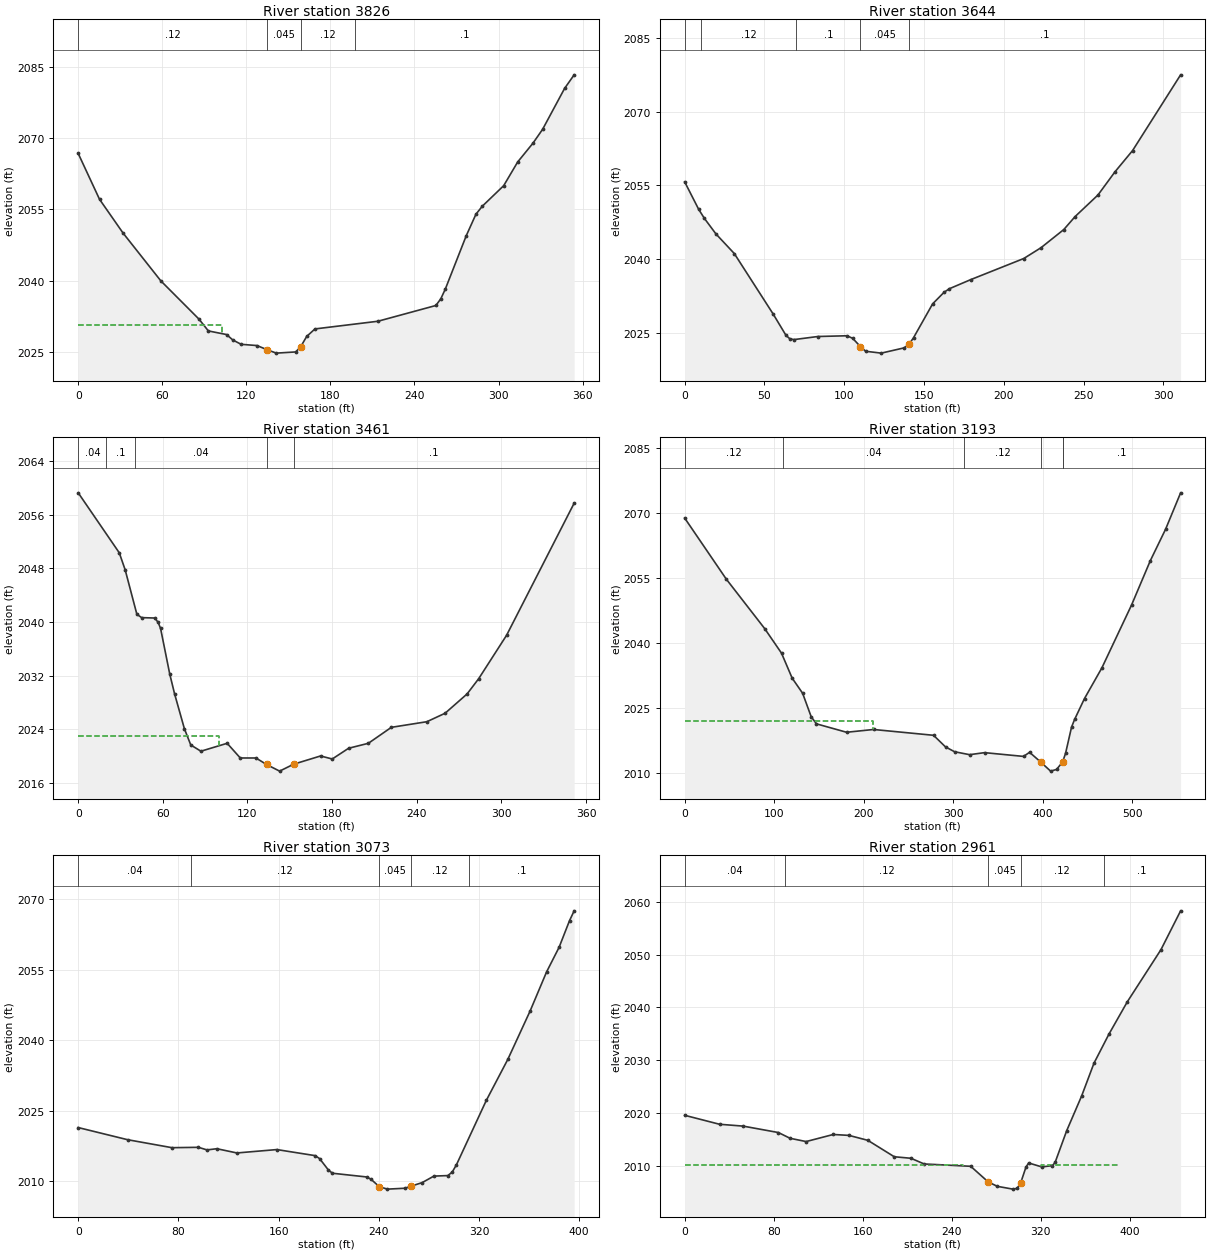
Type RM Length L Ch R = 1 ,3826    ,169.3,182.3,194.6
XS GIS Cut Line= 4
1952541.31134745207985.7056870721952465.68863597207967.738005052
1952282.79715263208027.5355049211952208.88777281207987.857895914
#Sta/Elev= 30
       0 2066.75    15.2 2057.14      32 2050.05      59    2040    86.2 2031.98
    92.9  2029.5   105.9 2028.74   110.3 2027.61   116.3 2026.69   127.6 2026.43
   134.5  2025.6   134.5 2025.59   141.4 2024.84   155.2 2025.09   158.7 2026.13
   163.1 2028.35     169 2029.92   213.9 2031.53   255.3 2034.84   258.8 2036.24
     262 2038.26     277  2049.5   283.9    2054   288.4 2055.67   303.7 2059.99
   313.7 2064.97   324.6 2068.91   331.5 2071.83   347.2 2080.42     354 2083.26
#Mann= 4 ,-1 , 0
       0     .12       0   134.5    .045       0   158.7     .12       0
  197.73      .1       0
#XS Ineff= 2 , 0
          102.54 2030.64
Permanent Ineff=
       F       F
Bank Sta=134.5,158.7
XS Rating Curve= 0 ,0
Exp/Cntr=0.3,0.1

Type RM Length L Ch R = 1 ,3644    ,177.3,183.2,188.8
XS GIS Cut Line= 2
1952557.64580895207870.475610555 1952272.3427851207747.276577526
#Sta/Elev= 30
       0 2055.74     8.8 2050.12    12.4 2048.27    19.6 2045.12    31.1 2041.12
    55.3 2028.87    63.5 2024.44      66 2023.72    68.5 2023.58    83.5 2024.21
   101.8 2024.36   105.3 2023.83   110.1 2022.17   113.4  2021.2   123.2 2020.82
   137.5 2021.89   140.5 2022.58   143.4 2023.95   155.4 2030.87   162.5 2033.21
   165.8 2033.94   179.3 2035.81   212.5 2040.11   223.3 2042.31   237.6 2046.02
   244.7 2048.67     259 2053.06   269.7  2057.8   280.7 2062.12   310.8 2077.56
#Mann= 5 ,-1 , 0
       0     .04       0      10     .12       0      70      .1       0
   110.1    .045       0   140.5      .1       0
Bank Sta=110.1,140.5
XS Rating Curve= 0 ,0
Exp/Cntr=0.3,0.1

Type RM Length L Ch R = 1 ,3461    ,272.1,267.5,259.3
XS GIS Cut Line= 4
 1952664.3150774207769.7395042511952618.36112188207733.718789202
 1952455.3063221207596.1672081721952379.14596831207572.075648374
#Sta/Elev= 30
       0 2059.25    29.1 2050.31    33.3 2047.76    41.6 2041.13      45 2040.64
    54.3 2040.58    56.7 2039.92    58.4 2039.02    64.9 2032.22    68.3 2029.29
    75.3 2024.06    79.8 2021.65      87 2020.72   105.6  2021.9   114.9 2019.71
     126 2019.71   133.5 2018.74   142.8 2017.75   152.7 2018.78   171.8 2020.01
   180.1 2019.56   191.7 2021.16   205.7  2021.9     222 2024.28   247.2 2025.12
   260.1 2026.38   275.7 2029.26   283.9 2031.53   303.7 2038.01   351.6 2057.71
#Mann= 5 ,-1 , 0
       0     .04       0      20      .1       0      40     .04       0
   133.5    .045       0   152.7      .1       0
#XS Ineff= 2 , 0
             100    2023
Permanent Ineff=
       F       F
Bank Sta=133.5,152.7
XS Rating Curve= 0 ,0
Exp/Cntr=0.3,0.1

Type RM Length L Ch R = 1 ,3193    ,118.6,120.8,121
XS GIS Cut Line= 3
1952933.05454873207603.5210336811952787.47393952207511.067421434
1952413.81026534207432.914824868
#Sta/Elev= 30
       0 2068.79    46.5 2054.68    89.4 2043.25   108.2 2037.58   120.1 2031.81
   131.8 2028.31   141.4 2022.87   147.3 2021.24   180.9  2019.3   211.1 2019.94
   278.1  2018.6   291.5 2015.91   301.6  2014.8   318.4 2014.12   335.1 2014.59
   378.7 2013.72   385.4 2014.67   397.82012.431   408.9 2010.32   415.6 2010.71
   422.3 2012.44   425.6 2014.41   432.3 2020.48   435.7 2022.25   446.8  2027.1
   466.2 2034.17   499.4 2048.71   520.4 2058.97   537.4 2066.21   554.2 2074.62
#Mann= 6 ,-1 , 0
       0     .12       0     110     .04       0  312.46     .12       0
   397.8    .045       0   422.3     .12       0  422.46      .1       0
#XS Ineff= 2 , 0
          210.59 2021.87
Permanent Ineff=
       F       F
Bank Sta=397.8,422.3
XS Rating Curve= 0 ,0
Exp/Cntr=0.3,0.1

Type RM Length L Ch R = 1 ,3073    ,91,112.2,118.8
XS GIS Cut Line= 3
1952821.09912709207476.5655995571952671.38247843207373.212794248
1952465.80881351207313.610960256
#Sta/Elev= 30
       0 2021.43    39.4 2018.85    74.9 2017.15      96 2017.23   102.8 2016.68
   110.7 2016.93   126.7 2016.03   158.6 2016.75   189.2 2015.46   192.7 2014.84
   199.5  2012.5   202.9 2011.72   230.2 2010.93   233.7 2010.46   240.5 2008.84
   246.9 2008.34     261 2008.53   265.5 2008.95   274.6 2009.72     284 2011.11
   295.1 2011.22   298.6 2011.95     302 2013.51   325.9 2027.23     343 2035.91
   360.8 2046.19     374 2054.53     384 2059.77   392.3 2065.42     396 2067.51
#Mann= 5 ,-1 , 0
       0     .04       0      90     .12       0   240.5    .045       0
   265.5     .12       0  311.93      .1       0
Bank Sta=240.5,265.5
XS Rating Curve= 0 ,0
Exp/Cntr(USF)=0,0
Exp/Cntr=0.5,0.3

Type RM Length L Ch R = 1 ,2961    ,64.6,53.6,59.6
XS GIS Cut Line= 4
1952828.03136576207411.8492348341952677.17013327207352.789100406
1952570.25077603207190.1796021211952483.41505882207170.999515713
#Sta/Elev= 30
       0 2019.55    31.3 2017.85    52.5  2017.5    84.2 2016.28    94.7 2015.19
   109.1 2014.57   133.5 2015.91   147.6 2015.74   164.6  2014.8   188.3 2011.69
   203.3  2011.4   215.2 2010.32     257 2009.88   272.7 2006.92   280.9 2006.08
   294.9 2005.55   298.8  2005.7     302  2006.8   306.7 2009.76   309.1 2010.51
   320.9 2009.76   330.4 2010.01   332.8  2010.6   343.3 2016.66   356.6 2023.18
   367.8 2029.45   381.2 2034.94   397.7 2041.07     428 2050.98   445.6 2058.32
#Mann= 5 ,-1 , 0
       0     .04       0      90     .12       0   272.7    .045       0
     302     .12       0  376.62      .1       0
#XS Ineff= 4 ,-1
       0     250  2010.2     250   252.7  2009.7     310     320  2009.7
     320   389.5  2010.2
Permanent Ineff=
       F       F       F       F
Bank Sta=272.7,302
XS Rating Curve= 0 ,0
Exp/Cntr(USF)=0,0
Exp/Cntr=0.5,0.3

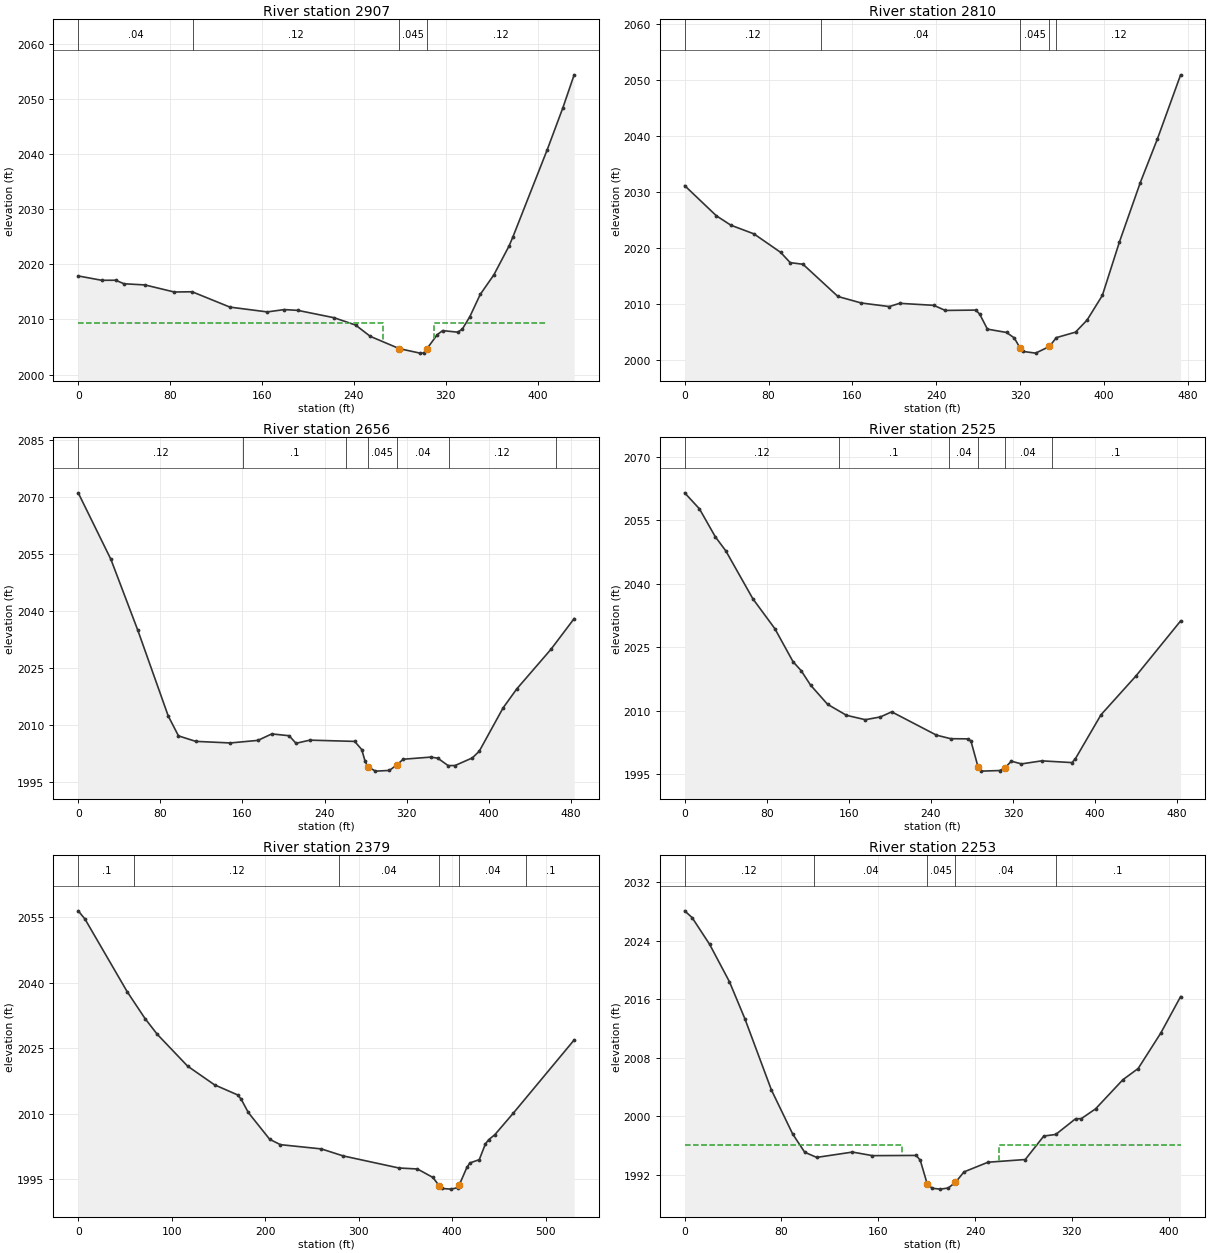
Type RM Length L Ch R = 1 ,2907    ,101.1,96.6,82.3
XS GIS Cut Line= 4
1952831.55433003207382.8862704151952719.43465193207329.120969954
1952599.11472615207148.303802825   1952510.00473 207133.81712684
#Sta/Elev= 30
       0 2017.88    20.5 2017.09    32.6  2017.1    39.9 2016.46    58.1 2016.25
    83.6 2014.97    99.2 2015.01   132.1 2012.23   164.6 2011.36   179.4 2011.78
   191.2 2011.64   222.7 2010.31   241.5 2008.98   254.3 2006.93   279.6  2004.7
   297.6 2003.89   300.8 2003.91   303.6 2004.68   312.6 2007.24   317.3 2007.97
   330.4 2007.69   334.4 2008.23     341 2010.51     350 2014.52   361.9 2018.08
   375.2 2023.34   378.5 2024.97   408.4 2040.78     422 2048.37   431.8 2054.33
#Mann= 4 ,-1 , 0
       0     .04       0     100     .12       0   279.6    .045       0
   303.6     .12       0
#XS Ineff= 2 ,-1
       0     265  2009.4     310 408.258  2009.4
Permanent Ineff=
       F       F
Bank Sta=279.6,303.6
XS Rating Curve= 0 ,0
Exp/Cntr(USF)=0,0
Exp/Cntr=0.5,0.3

Type RM Length L Ch R = 1 ,2810    ,158.3,154.6,149.6
XS GIS Cut Line= 4
1952939.62142987207293.4838147641952836.30561023 207192.08180066
1952608.60295261207079.9522422521952533.91609362207080.050827351
#Sta/Elev= 30
       0 2031.12    30.2 2025.74    44.1 2024.05    66.1  2022.5    91.5 2019.21
   100.7 2017.36   112.9 2017.07   146.3 2011.31   168.5 2010.15   195.3 2009.51
   205.1 2010.09   237.7 2009.73   248.7 2008.82   277.9 2008.88   281.6 2008.14
   288.9 2005.48   307.2 2004.88   314.5 2003.91   320.2 2002.08   322.7  2001.5
   334.9 2001.19   348.1 2002.38   354.7 2003.96     373 2004.94     384 2007.09
   398.6  2011.5   414.9 2021.05   434.8 2031.66     451 2039.39   473.3 2050.92
#Mann= 5 ,-1 , 0
       0     .12       0     130     .04       0   320.2    .045       0
   348.1     .04       0  354.76     .12       0
Bank Sta=320.2,348.1
XS Rating Curve= 0 ,0
Exp/Cntr(USF)=0,0
Exp/Cntr=0.3,0.1

Type RM Length L Ch R = 1 ,2656    ,135.5,130.3,125.3
XS GIS Cut Line= 4
1953001.18774685207013.003838615 1952910.3458103207007.431789154
1952613.74521446206938.6449358861952527.29281008206953.222468357
#Sta/Elev= 30
       0 2071.07    31.8  2053.6    58.1  2034.9    87.7 2012.38    97.7 2007.14
   114.5  2005.7   148.2 2005.28   175.1 2005.96   188.6 2007.66   205.5 2007.18
   212.2 2005.19   225.7 2006.02   269.4 2005.69   276.2 2003.55   279.5 2000.49
   282.1 1999.05   289.6 1997.87   303.1 1998.05   310.5  1999.5   316.6    2001
   343.5 2001.56   350.3 2001.28   360.4 1999.33   367.1 1999.34     384 2001.35
   390.7 2003.09     414 2014.52   427.3  2019.5   460.6 2029.91   483.2 2037.99
#Mann= 7 ,-1 , 0
       0     .12       0  161.01      .1       0  261.01     .04       0
   282.1    .045       0   310.5     .04       0  361.01     .12       0
  465.49      .1       0
Bank Sta=282.1,310.5
XS Rating Curve= 0 ,0
Exp/Cntr=0.3,0.1

Type RM Length L Ch R = 1 ,2525    ,144.7,146.8,139.9
XS GIS Cut Line= 3
1952982.31995803206926.7627522621952787.90317217206828.709068959
1952522.48199495206838.852553439
#Sta/Elev= 30
       0 2061.48    14.4 2057.69    29.9 2051.07    40.1 2047.76    66.5 2036.41
    87.9 2029.36   105.6 2021.56   113.6 2019.41   122.7 2016.01   139.3 2011.47
   157.7 2008.87   176.1 2007.83   190.8 2008.49   201.8 2009.69   245.4 2004.18
   259.3 2003.34   275.7  2003.3     279 2002.81     2861996.628   288.9 1995.67
     307 1995.81   311.8 1996.36   318.4 1998.02   328.3 1997.38     348  1998.1
   377.5 1997.69   380.8 1998.59   405.8    2009   439.9 2018.19   483.4 2031.19
#Mann= 6 ,-1 , 0
       0     .12       0     150      .1       0  257.74     .04       0
     286    .045       0   311.8     .04       0  357.74      .1       0
Bank Sta=286,311.8
XS Rating Curve= 0 ,0
Exp/Cntr(USF)=0,0
Exp/Cntr=0.3,0.1

Type RM Length L Ch R = 1 ,2379    ,124.3,125.6,125.3
XS GIS Cut Line= 3
1952991.61815214206574.2766665951952776.91439732206701.070222591
1952497.96857413206735.727127896
#Sta/Elev= 30
       0 2056.42     7.2 2054.55    52.4  2037.9    71.5 2031.76    84.6 2028.15
     117 2020.88   145.8  2016.6   170.5 2014.29   174.3 2013.31   181.9 2010.27
   204.8 2004.13   216.2 2002.91   260.1 2001.93   283.4 2000.33   342.9 1997.57
   362.8 1997.34   379.3 1995.41   385.9 1993.55   389.2 1992.88   398.7 1992.73
   405.8 1993.06   407.5 1993.67   415.7 1997.71     419 1998.73   428.9 1999.47
   435.5 2003.08   438.8    2004   445.7 2005.22   465.3 2010.11   530.4 2026.87
#Mann= 6 ,-1 , 0
       0      .1       0      60     .12       0  279.35     .04       0
   385.9    .045       0   407.5     .04       0  479.35      .1       0
Bank Sta=385.9,407.5
XS Rating Curve= 0 ,0
Exp/Cntr(USF)=0,0
Exp/Cntr=0.3,0.1

Type RM Length L Ch R = 1 ,2253    ,149,141.5,135
XS GIS Cut Line= 4
1952833.03788295206533.8618481061952775.33991247 206584.41809459
1952525.19682597 206606.006743671952476.31433223206671.971474695
#Sta/Elev= 30
       0 2028.09     6.2 2027.15    20.6 2023.51      37 2018.39    49.8 2013.31
    71.7 2003.58    89.3 1997.55    99.2 1995.07   109.1 1994.36   138.7 1995.09
   155.2  1994.6   191.4 1994.63   194.7 1993.97   200.5 1990.72   204.6 1990.14
   211.2 1990.02   217.8 1990.17   223.8 1990.95   230.9 1992.38   250.7  1993.7
   281.5 1994.07   296.8 1997.28   306.7  1997.5   323.1 1999.65   327.8 1999.66
   339.6    2001   362.2 2004.99   374.8 2006.52   393.5 2011.37   409.9 2016.36
#Mann= 5 ,-1 , 0
       0     .12       0  106.71     .04       0   200.5    .045       0
   223.8     .04       0  306.71      .1       0
#XS Ineff= 2 , 0
             180    1996     260            1996
Permanent Ineff=
       F       F
Bank Sta=200.5,223.8
XS Rating Curve= 0 ,0
Exp/Cntr=0.3,0.1

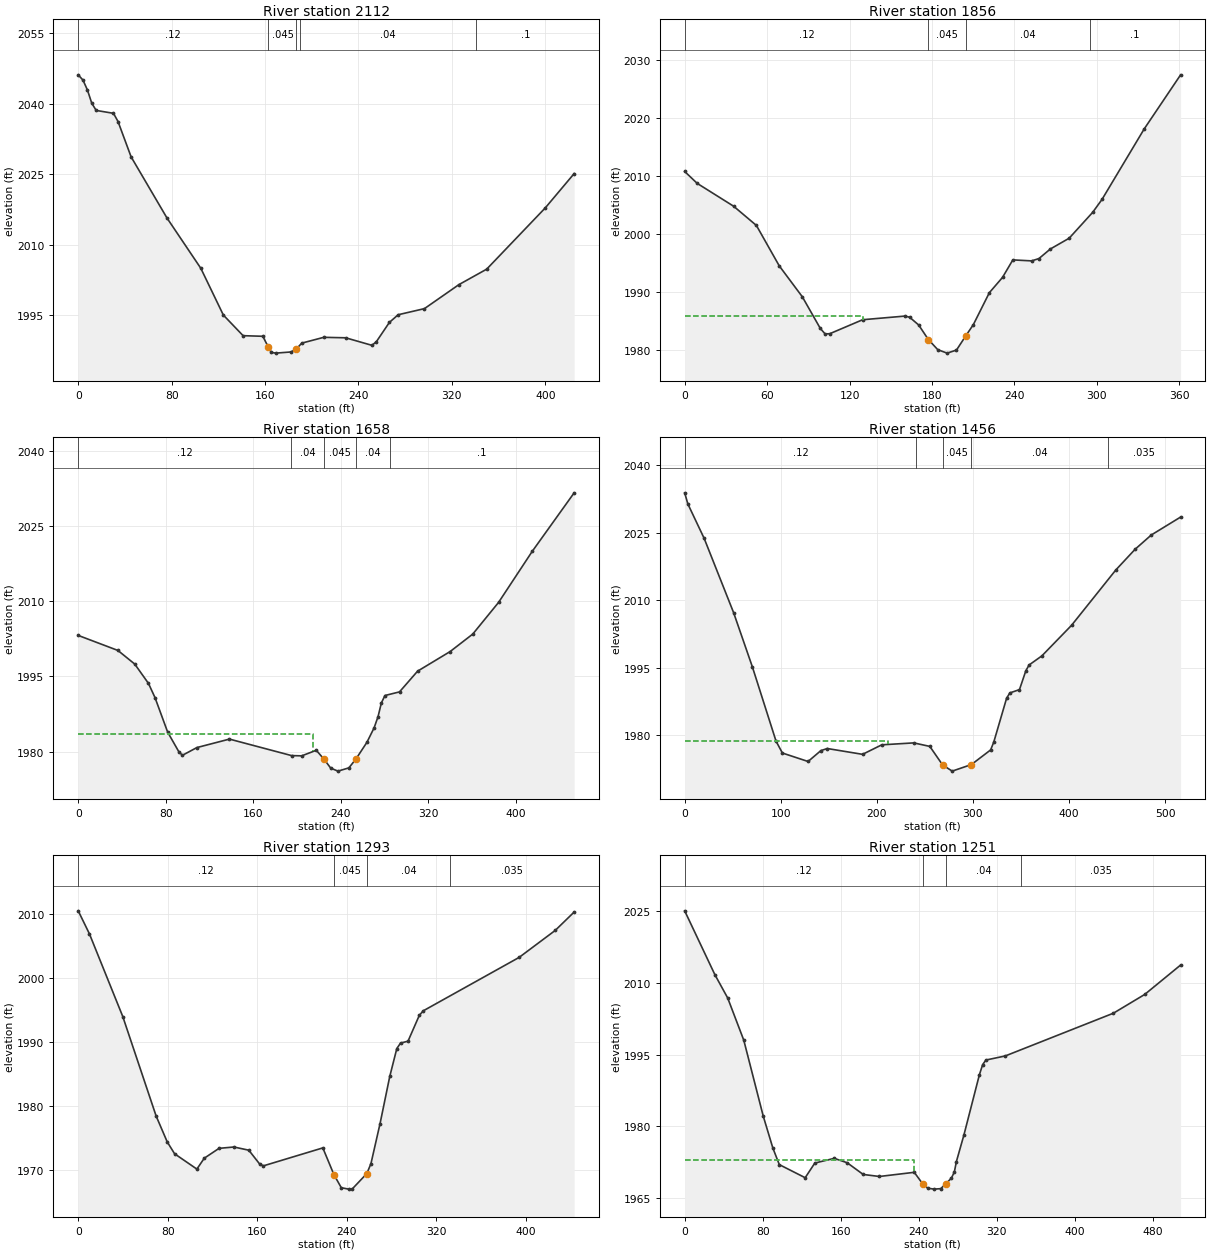
Type RM Length L Ch R = 1 ,2112    ,246.4,255.4,257
XS GIS Cut Line= 3
1952753.24626687206376.4787192431952481.06276666 206526.94040569
1952372.02030851206559.061439876
#Sta/Elev= 30
       0 2046.13     4.1    2045     7.9  2042.9    11.6  2040.1    15.4 2038.56
    30.2 2037.95    34.1  2036.2    45.3 2028.69      76  2015.7     105    2005
   124.3 1995.06   141.2 1990.68   158.1 1990.55   162.9 1988.19   165.4 1987.13
   169.1 1986.97   182.3 1987.22   186.91987.897   191.5  1989.1   210.3 1990.33
     229 1990.23   251.5 1988.63   255.3 1989.39   266.5 1993.51     274 1995.13
   296.5 1996.43     326 2001.53   349.8 2004.82     400 2017.85   424.7 2025.14
#Mann= 5 ,-1 , 0
       0     .12       0   162.9    .045       0   186.9     .12       0
     190     .04       0     341      .1       0
Bank Sta=162.9,186.9
XS Rating Curve= 0 ,0
Exp/Cntr(USF)=0,0
Exp/Cntr=0.3,0.1

Type RM Length L Ch R = 1 ,1856    ,194.8,198.5,200.8
XS GIS Cut Line= 3
1952640.53930945206272.6475008841952546.91854786206258.562215502
1952291.09606518206332.425039928
#Sta/Elev= 30
       0  2010.8     9.1 2008.75    35.6 2004.81    52.2 2001.49    68.8 1994.53
    85.6 1989.19    98.7 1983.73   102.2 1982.78   105.6 1982.82   129.5 1985.23
   160.3 1985.86   163.7 1985.66   170.3 1984.32   177.3 1981.82   184.2 1980.06
     191 1979.47   197.8    1980   204.7  1982.5   210.1  1984.4   221.7 1989.89
   231.3 1992.53   238.8 1995.55   252.5 1995.38   257.8 1995.78   266.1 1997.43
   279.8 1999.29   296.9 2003.75   303.7 2005.98   334.4 2018.14   360.9 2027.47
#Mann= 4 ,-1 , 0
       0     .12       0   177.3    .045       0   204.7     .04       0
  294.67      .1       0
#XS Ineff= 2 , 0
          130.03  1985.9
Permanent Ineff=
       F       F
Bank Sta=177.3,204.7
XS Rating Curve= 0 ,0
Exp/Cntr=0.3,0.1

Type RM Length L Ch R = 1 ,1658    ,195.3,201.3,207.3
XS GIS Cut Line= 4
1952618.64211274206131.8811497371952553.16765005206077.700385221
1952296.84159896206110.8529659621952206.04667646206173.130985908
#Sta/Elev= 30
       0 2003.19    36.3 2000.19    51.7 1997.47    64.2 1993.63    70.2 1990.79
    81.8 1983.89      92 1979.98    95.3 1979.27   108.5 1980.81   138.3  1982.5
   195.1 1979.21   204.4 1979.16   217.7 1980.27   224.8 1978.48   230.9 1976.71
   237.5 1976.11   247.5 1976.76   254.1 1978.57     264 1981.86   270.6 1984.76
   274.2    1987   277.2 1989.71   280.5  1991.2   293.8 1991.92   310.3 1996.05
   340.1 1999.97   360.8 2003.46   384.4 2009.78   415.1 2019.94   453.5 2031.64
#Mann= 5 ,-1 , 0
       0     .12       0  194.99     .04       0   224.8    .045       0
   254.1     .04       0  284.99      .1       0
#XS Ineff= 2 , 0
             215  1983.5
Permanent Ineff=
       F       F
Bank Sta=224.8,254.1
XS Rating Curve= 0 ,0
Exp/Cntr=0.3,0.1

Type RM Length L Ch R = 1 ,1456    ,164.1,163.7,162.1
XS GIS Cut Line= 4
1952687.25427657205907.3528385191952599.25782328205931.343870245
1952314.63078863205880.4020998391952181.74370229205908.043152086
#Sta/Elev= 30
       0 2033.85     3.3 2031.38    20.3 2023.72    50.9 2007.25    70.5 1995.17
    95.1 1978.69   101.7 1976.07   128.4 1974.19   141.7  1976.6   148.4 1977.07
   185.1 1975.78   205.1 1977.89   238.4 1978.32   255.1 1977.54   268.4 1973.43
   278.4 1972.05   298.4 1973.51   318.4 1976.76   321.7 1978.53     335 1988.23
   338.4 1989.42   348.4 1990.15     355 1994.32   358.4 1995.62   371.7 1997.64
   402.6 2004.43   448.7 2016.73   468.8 2021.33   485.6 2024.49   516.1 2028.47
#Mann= 5 ,-1 , 0
       0     .12       0  241.21     .04       0   268.4    .045       0
   298.4     .04       0  440.36    .035       0
#XS Ineff= 2 , 0
          211.27 1978.71
Permanent Ineff=
       F       F
Bank Sta=268.4,298.4
XS Rating Curve= 0 ,0
Exp/Cntr=0.3,0.1

Type RM Length L Ch R = 1 ,1293    ,41.6,41.8,42.2
XS GIS Cut Line= 3
1952674.31564961205767.5172762011952374.57568324205728.718448066
1952245.24625612205784.254025593
#Sta/Elev= 30
       0 2010.54      10 2006.95    39.8 1994.03    69.6 1978.49    79.5 1974.45
    86.1 1972.59     106  1970.2   112.6  1971.9   125.8 1973.44   139.1 1973.65
   152.4 1973.15   162.2 1970.96   165.5 1970.71   218.5 1973.51   228.4 1969.34
     235 1967.29   241.6 1967.07   244.9 1967.12   257.8  1969.5   261.5 1971.06
   269.6 1977.29   278.3 1984.68   284.6 1989.03   287.9 1989.88   294.6 1990.18
   304.7 1994.22   308.2 1994.92   393.9 2003.27   426.1 2007.48     443 2010.35
#Mann= 4 ,-1 , 0
       0     .12       0   228.4    .045       0   257.8     .04       0
  332.24    .035       0
Bank Sta=228.4,257.8
XS Rating Curve= 0 ,0
Exp/Cntr(USF)=0,0
Exp/Cntr=0.3,0.1

Type RM Length L Ch R = 1 ,1251    ,154.3,153,153.5
XS GIS Cut Line= 3
 1952694.9636629205728.0493814911952363.08611499205685.392108732
1952204.40767898 205756.06741433
#Sta/Elev= 30
       0 2025.09    30.9 2011.74    44.1 2006.83    60.6 1997.98    80.5 1982.11
    90.4  1975.4      97 1971.94   123.5  1969.2   133.4 1972.27   153.3 1973.25
   166.5 1972.34     183 1969.88   199.6 1969.46   235.3 1970.33   244.1 1967.87
   249.2    1967   255.8 1966.81   262.4 1966.91   267.6 1967.91   273.4 1969.13
   276.4 1970.41   278.5 1972.59   286.1 1978.07   302.1 1990.79   305.4 1992.88
   308.7 1993.84   328.6  1994.7   439.4 2003.65   471.5 2007.58   508.3 2013.74
#Mann= 4 ,-1 , 0
       0     .12       0   244.1    .045       0   267.6     .04       0
  344.61    .035       0
#XS Ineff= 2 , 0
             235    1973
Permanent Ineff=
       F       F
Bank Sta=244.1,267.6
XS Rating Curve= 0 ,0
Exp/Cntr=0.3,0.1

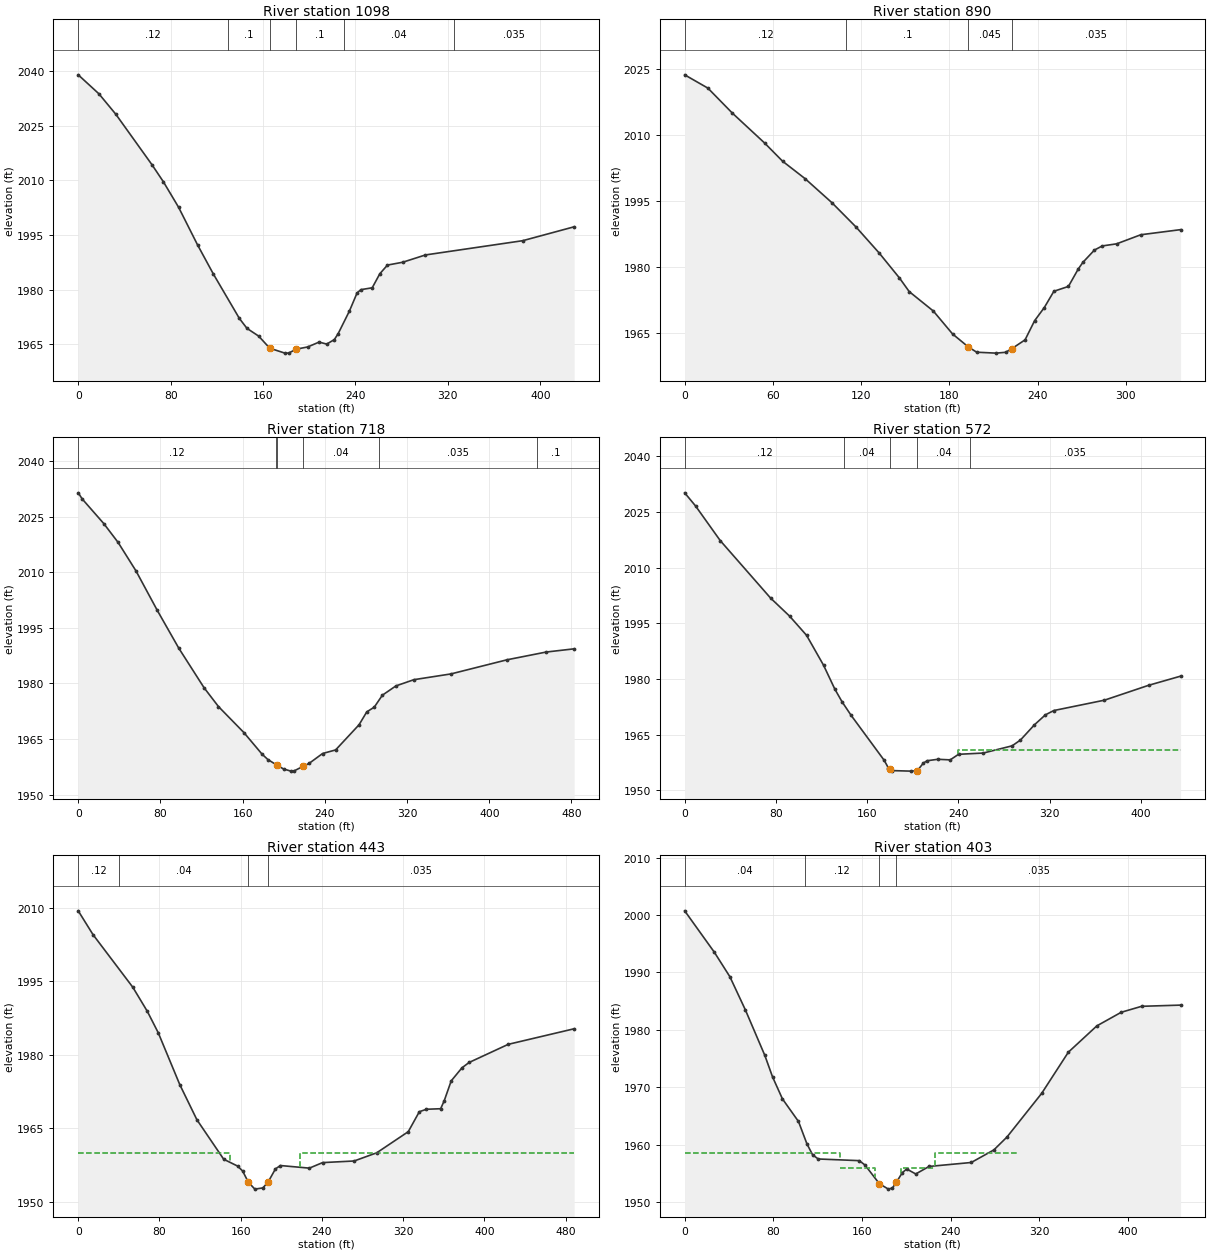
Type RM Length L Ch R = 1 ,1098    ,208.3,207.5,207.8
XS GIS Cut Line= 3
1952678.88718485205567.6431240471952364.60625507205547.890858185
1952255.25242036  205581.3473534
#Sta/Elev= 30
       0 2038.92    17.9 2033.72    32.5 2028.13    63.9 2014.24    73.7  2009.6
    86.9 2002.59   103.3 1992.28     117 1984.28   139.5 1972.11   146.1 1969.38
   156.2 1967.26   165.8 1963.94   178.9 1962.59   182.2 1962.61   188.8 1963.68
   198.7 1964.29   208.5 1965.62   215.1 1965.07   221.7  1966.3     225 1967.92
   234.8 1974.16   241.4  1979.1   244.7    1980   254.5 1980.51   261.1 1984.37
   267.7 1986.74   280.8 1987.51   300.6 1989.52   384.8 1993.43   429.3 1997.24
#Mann= 6 ,-1 , 0
       0     .12       0     130      .1       0   165.8    .045       0
   188.8      .1       0     230     .04       0   324.9    .035       0
Bank Sta=165.8,188.8
XS Rating Curve= 0 ,0
Exp/Cntr=0.3,0.1

Type RM Length L Ch R = 1 ,890     ,179.7,172.3,166.8
XS GIS Cut Line= 3
1952636.55159639205439.0244121461952528.94476208205359.321365418
1952325.61437046205363.158871008
#Sta/Elev= 30
       0 2023.61    15.8 2020.59    32.3 2014.96    54.4 2008.12    66.6    2004
    81.9 2000.04   100.1  1994.6   116.5 1989.08   132.3 1983.16   146.1 1977.49
   152.7 1974.41   169.1    1970   182.2 1964.79   192.91961.846   198.6 1960.65
   211.8 1960.44   218.3 1960.63   222.51961.454   231.5 1963.45     238  1967.8
   244.6 1970.79   251.1 1974.48     261 1975.58   267.6 1979.49   270.8 1981.03
   278.7 1983.84     284 1984.77   293.8 1985.25   310.2 1987.31   337.3 1988.47
#Mann= 4 ,-1 , 0
       0     .12       0     110      .1       0   192.9    .045       0
   222.5    .035       0
Bank Sta=192.9,222.5
XS Rating Curve= 0 ,0
Exp/Cntr=0.3,0.1

Type RM Length L Ch R = 1 ,718     ,146.5,146.2,144.6
XS GIS Cut Line= 4
1952628.78352997205117.689940109 1952532.0447428205151.501555041
1952332.93189931 205229.456111691952228.67941994205359.067302263
#Sta/Elev= 30
       0 2031.42       4 2029.73    24.9 2023.12    38.8 2018.05    56.2 2010.37
      77 1999.68    97.9  1989.5   122.5 1978.83   136.5 1973.76   161.2 1966.76
   178.8 1960.96   184.6 1959.46   193.11958.014   199.8 1956.93     207 1956.35
     210  1956.4   218.61957.608   224.6 1958.42   237.8  1961.1   250.5 1962.07
   273.3 1968.86   280.8 1972.33   288.1 1973.61     296 1976.84   309.2 1979.34
   326.7 1981.02   362.7 1982.57   417.4 1986.39   455.3 1988.47   482.6 1989.34
#Mann= 6 ,-1 , 0
       0     .12       0  192.48     .06       0   193.1    .045       0
   218.6     .04       0  292.48    .035       0  446.31      .1       0
Bank Sta=193.1,218.6
XS Rating Curve= 0 ,0
Exp/Cntr(USF)=0,0
Exp/Cntr=0.3,0.1

Type RM Length L Ch R = 1 ,572     ,137.4,128.9,116.8
XS GIS Cut Line= 4
1952574.94675425204970.075358465 1952474.0352959205013.478136256
1952301.10054475 205094.22177051 1952181.0665459205154.537164032
#Sta/Elev= 30
       0 2030.14     9.5 2026.62    31.2 2017.27    75.3 2001.81      92 1996.94
   106.9 1991.77   121.8 1983.72   131.7 1977.28     138 1973.88     146 1970.21
     175  1958.1   178.6 1956.09   180.31955.702   182.2 1955.33   198.3 1955.19
     204 1955.29   209.4 1957.37   212.7 1957.99   222.1 1958.38   232.9 1958.22
   240.2 1959.72   261.9 1960.06   287.2    1962   294.5 1963.56   306.8 1967.67
   316.4 1970.35   323.8 1971.51   368.2  1974.3     407 1978.31     435 1980.77
#Mann= 5 ,-1 , 0
       0     .12       0  139.85     .04       0   180.3    .045       0
     204     .04       0  249.85    .035       0
#XS Ineff= 2 , 0
                             240            1961
Permanent Ineff=
       F       F
Bank Sta=180.3,204
XS Rating Curve= 0 ,0
Exp/Cntr(USF)=0,0
Exp/Cntr=0.5,0.3

Type RM Length L Ch R = 1 ,443     ,41.3,40.2,43
XS GIS Cut Line= 5
1952484.26026696204829.9856593911952376.62137806204875.558576062
1952340.59707251204955.8537149431952303.81287968205070.293426052
1952150.68460149205127.410427928
#Sta/Elev= 30
       0 2009.42    14.6 2004.55    53.8  1993.8    68.1 1988.87    78.8 1984.52
   100.1 1973.88   116.9 1966.73   143.3 1958.66   157.1 1957.25     162 1956.24
   167.51953.979     174 1952.55   181.9  1952.8   187.11954.023   194.3 1956.69
   199.2 1957.37   227.7 1956.84   240.7 1957.97   271.8  1958.3   294.1 1959.98
   325.1 1964.29     336 1968.37     343 1968.87     357 1968.98   360.5  1970.6
   367.4 1974.67     378 1977.34     385 1978.43   423.6 1982.14   488.5 1985.32
#Mann= 4 ,-1 , 0
       0     .12       0      40     .04       0   167.5    .045       0
   187.1    .035       0
#XS Ineff= 4 ,-1
       0     150    1960     150   157.5  1956.9   197.1     218  1956.9
     218  488.53    1960
Permanent Ineff=
       F       F       F       F
Bank Sta=167.5,187.1
XS Rating Curve= 0 ,0
Exp/Cntr(USF)=0,0
Exp/Cntr=0.5,0.3

Type RM Length L Ch R = 1 ,403     ,105.5,113.3,119
XS GIS Cut Line= 6
1952443.46165586204778.3363538381952360.69706547204808.808771238
1952319.36124456204914.3898791671952287.36902067204968.453999832
1952265.39962748 205030.346775741952160.45022646205082.922580689
#Sta/Elev= 30
       0 2000.73    26.8 1993.51    40.8 1989.25    54.8 1983.46    72.3 1975.56
    79.3  1971.8    88.2 1967.98   102.7 1964.04   110.3 1960.15   115.4 1958.24
   120.5 1957.51   157.5 1957.22   162.7 1956.46   175.71953.198   183.8 1952.26
   187.5 1952.47   191.11953.476   196.3  1955.1   200.3 1955.77   208.5  1954.9
   220.5 1956.21   258.6  1956.9     279 1959.09   290.8 1961.33   322.1 1968.93
   346.2 1976.11   371.9 1980.69   393.9 1983.06   412.3  1984.1   447.5 1984.31
#Mann= 4 ,-1 , 0
       0     .04       0   108.2     .12       0   175.7    .045       0
   191.1    .035       0
#XS Ineff= 4 ,-1
       0     140  1958.5     140   171.3 1955.95   195.4     226 1955.95
     226     300  1958.5
Permanent Ineff=
       F       F       F       F
Bank Sta=175.7,191.1
XS Rating Curve= 0 ,0
Exp/Cntr(USF)=0,0
Exp/Cntr=0.5,0.3

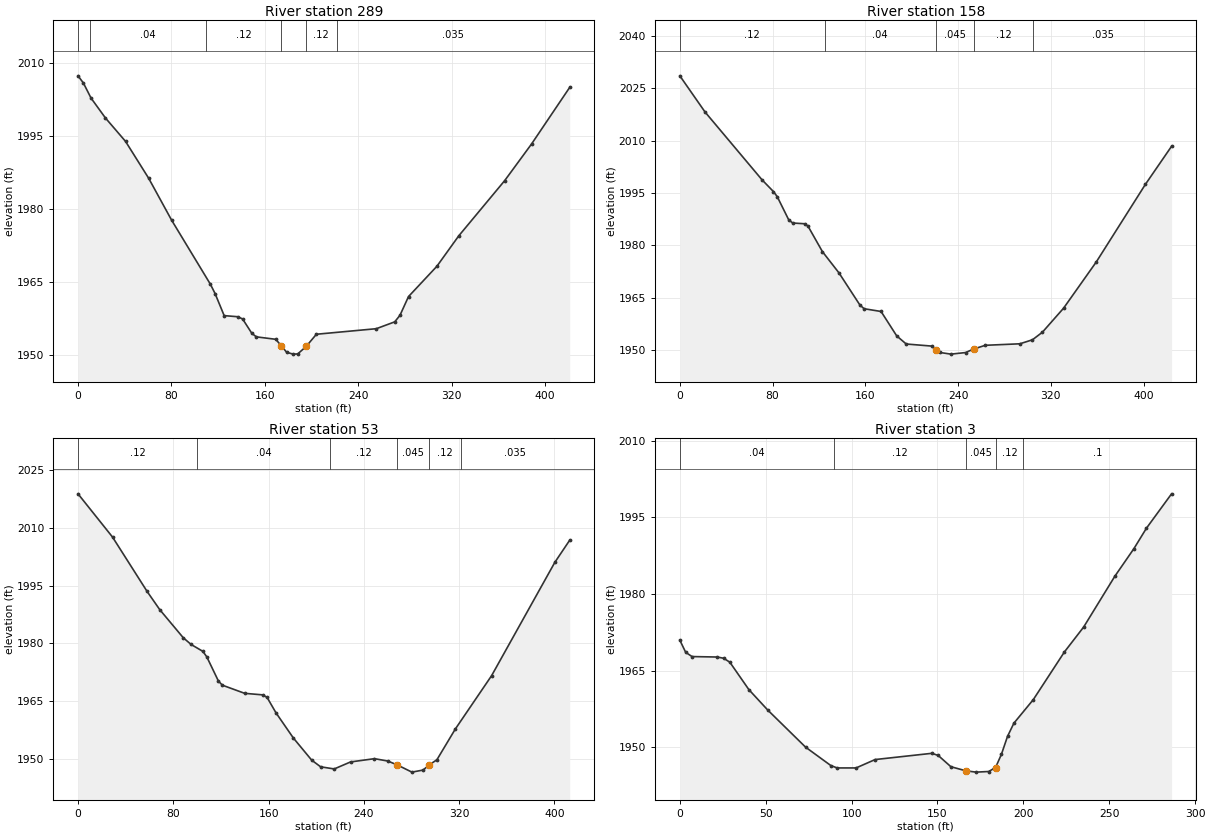
Type RM Length L Ch R = 1 ,289     ,131.1,131.5,133.4
XS GIS Cut Line= 4
 1952455.7415608204759.0005850671952344.39740548204753.760860111
 1952183.9308287204861.1752217091952067.34694843204857.900393612
#Sta/Elev= 30
       0 2007.36     4.6 2005.89    11.2 2002.77    23.5 1998.69    40.7 1993.88
    60.5  1986.3    80.2 1977.66   113.4 1964.49   117.4 1962.58   125.2 1958.03
     137  1957.8     141 1957.34   148.9 1954.39   152.8 1953.66   169.4 1953.16
   174.1 1951.83   178.8 1950.47   184.4 1950.11   188.2 1950.15   195.4 1951.68
   204.2  1954.2   255.5 1955.34   271.3 1956.75   275.8  1958.1   283.1 1961.95
   307.4 1968.18   326.1 1974.43   365.5 1985.81   388.5 1993.34   421.2 2004.99
#Mann= 6 ,-1 , 0
       0     .12       0      10     .04       0     110     .12       0
   174.1    .045       0   195.4     .12       0  221.47    .035       0
Bank Sta=174.1,195.4
XS Rating Curve= 0 ,0
Exp/Cntr(USF)=0,0
Exp/Cntr=0.3,0.1

Type RM Length L Ch R = 1 ,158     ,107.2,105,103.9
XS GIS Cut Line= 4
1952472.77066691204606.3935957221952377.80065208204607.048561341
1952164.28186012204707.9132667451952071.27674215204711.843060462
#Sta/Elev= 30
       0 2028.56    21.7 2018.21    70.9 1998.76    80.7 1995.41      84 1993.95
    93.9 1987.31    97.4 1986.38   108.2 1986.16   110.7  1985.4     123 1978.18
   137.3 1972.08   155.4 1962.85     159 1961.82   173.6 1961.03   187.1 1954.03
   195.3 1951.71   217.1 1951.12   220.7 1950.11   224.4 1949.28   233.9 1948.81
   246.5 1949.26   253.4 1950.27   263.5 1951.34   293.3 1951.77   304.2 1952.92
   312.8  1955.1     331 1961.96   359.3 1975.25   401.7  1997.5   424.2 2008.37
#Mann= 5 ,-1 , 0
       0     .12       0  124.97     .04       0   220.7    .045       0
   253.4     .12       0  304.97    .035       0
Bank Sta=220.7,253.4
XS Rating Curve= 0 ,0
Exp/Cntr(USF)=0,0
Exp/Cntr=0.3,0.1

Type RM Length L Ch R = 1 ,53      ,49.4,50.2,51.4
XS GIS Cut Line= 4
1952453.77666394204512.0785465131952332.60802433204501.599096601
1952154.45737583204600.4989051461952068.00191405204613.598217536
#Sta/Elev= 30
       0 2018.89      29 2007.63      58  1993.5    68.6 1988.77    88.3 1981.47
    94.9 1979.71   104.8 1977.91   108.1 1976.49   117.9 1970.17   121.2 1969.11
   139.9 1966.99     155 1966.59   158.7 1965.94   166.2 1961.92   180.8 1955.36
   196.2  1949.6   203.7 1947.87   215.1 1947.32   228.8 1949.14   248.9 1949.99
     260 1949.38   268.2 1948.34   280.3 1946.49   289.7 1947.03   294.7 1948.34
   301.3 1949.71   316.7 1957.68   347.2 1971.58   400.3 2001.07   412.8 2006.84
#Mann= 6 ,-1 , 0
       0     .12       0     100     .04       0  211.62     .12       0
   268.2    .045       0   294.7     .12       0  321.62    .035       0
Bank Sta=268.2,294.7
XS Rating Curve= 0 ,0
Exp/Cntr(USF)=0,0
Exp/Cntr=0.3,0.1

Type RM Length L Ch R = 1 ,3       ,,,
XS GIS Cut Line= 3
1952329.47004709 204454.155219571952112.10893595204563.877441794
1952073.91449153204583.321886241
#Sta/Elev= 30
       0 1970.98     3.4  1968.6     7.1 1967.77    21.8 1967.68    25.5 1967.44
    29.1 1966.67    40.2  1961.3    51.2  1957.3    73.2 1950.05    87.9 1946.45
    91.6 1945.98   102.6 1945.98   113.7 1947.62   146.7 1948.84   150.4 1948.43
   157.8 1946.22   166.7  1945.4   172.5 1945.16   179.8 1945.28   183.8 1946.05
   187.2 1948.61   190.8 1952.17   194.5 1954.74   205.8 1959.35   223.9 1968.67
   235.1 1973.54   253.3  1983.5   264.4  1988.9   271.7  1992.9   286.3 1999.61
#Mann= 5 ,-1 , 0
       0     .04       0      90     .12       0   166.7    .045       0
   183.8     .12       0     200      .1       0
Bank Sta=166.7,183.8
XS Rating Curve= 0 ,0
Exp/Cntr(USF)=0,0
Exp/Cntr=0.3,0.1
LCMann Table=0

Chan Stop Cuts=-1
Use User Specified Reach Order=0
Composite Channel Slope=5